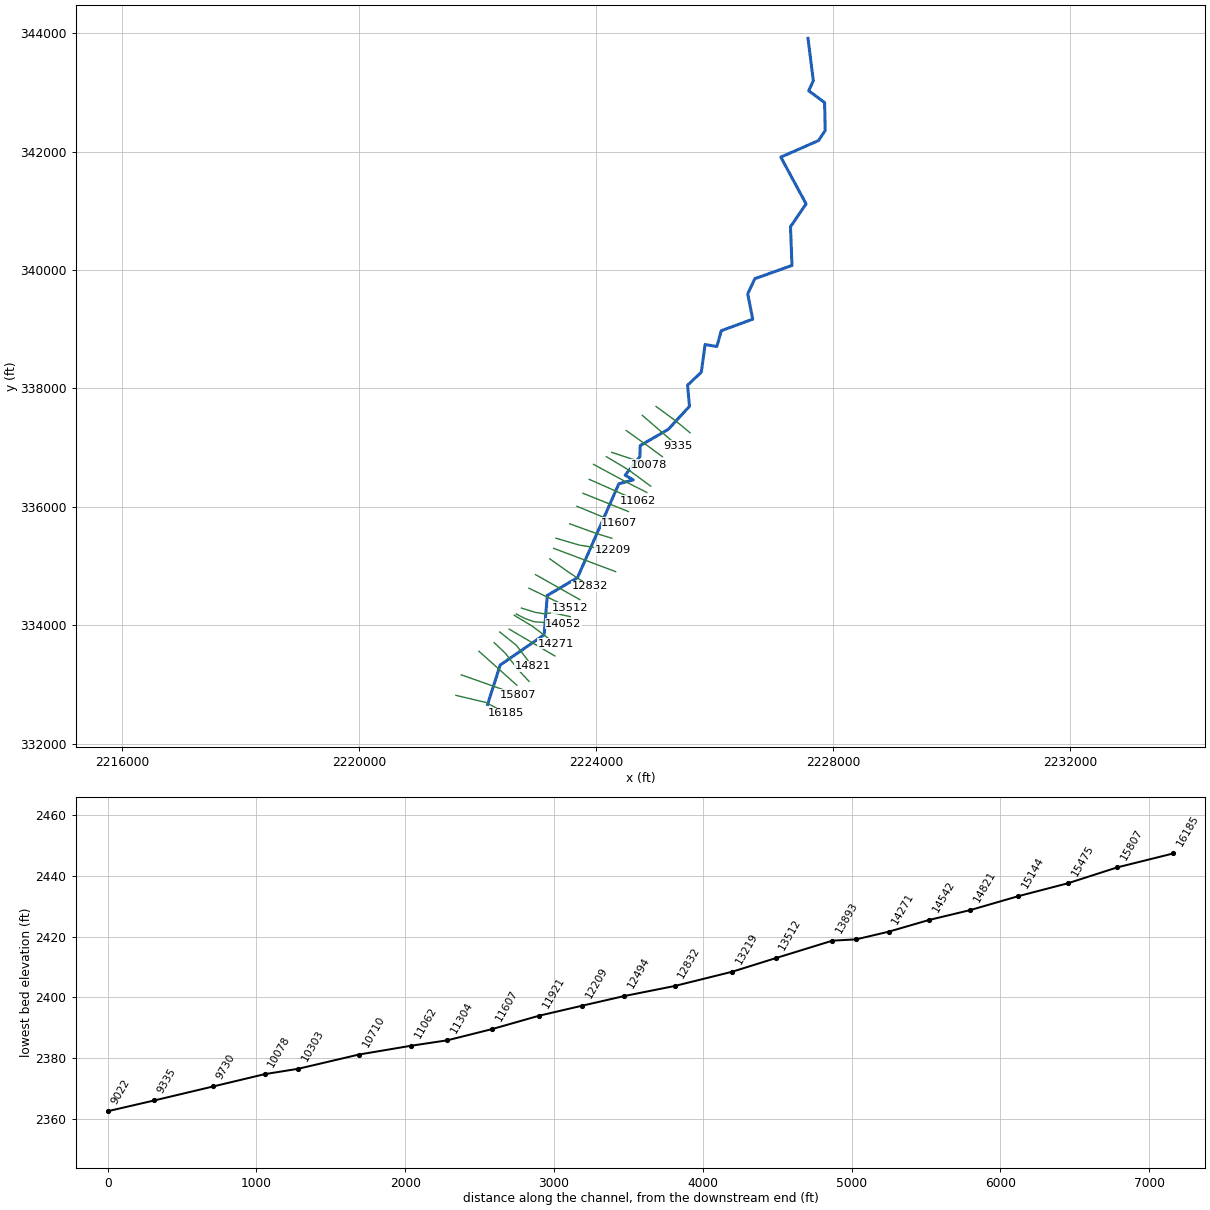
--- LAURELRN2.prj (project) ---

Proj Title=LAURELRN2
Current Plan=p01
Default Exp/Contr=0.3,0.1
English Units
Geom File=g01
Flow File=f01
Plan File=p01
Y Axis Title=Elevation
X Axis Title(PF)=Main Channel Distance
X Axis Title(XS)=Station
BEGIN DESCRIPTION:
Stream Name- Laurel Run 2
Flood Zone: Zone A
Greenbrier County, WV
County-Wide Study
WVDHSEM-2018-3, Flood Risk Project
HEC-RAS Version: 5.0.7
General Notes:
For the Hydrology Regression was used.
END DESCRIPTION:
DSS Export Rating Curves= 0
DSS Export Rating Curve Sorted= 0
DSS Export Volume Flow Curves= 0
DXF Filename=A2c.
DXF OffsetX= 0
DXF OffsetY= 0
DXF ScaleX= 1
DXF ScaleY= 10

--- LAURELRN2.p01 (plan) ---

Plan Title=Floodplain
Program Version=5.07
Short Identifier=Floodplain
Geom File=g01
Flow File=f01
Subcritical Flow
K Sum by GR= 0
Std Step Tol= 0.01
Critical Tol= 0.01
Num of Std Step Trials= 20
Max Error Tol= 0.3
Flow Tol Ratio= 0.001
Split Flow NTrial= 30
Split Flow Tol= 0.02
Split Flow Ratio= 0.02
Log Output Level= 0
Friction Slope Method= 1
Unsteady Friction Slope Method= 2
Unsteady Bridges Friction Slope Method= 1
Parabolic Critical Depth
Global Vel Dist= 0 , 0 , 0
Global Log Level= 0
CheckData=True
Encroach Param=-1 ,0,0, 0
Computation Interval=1MIN
Output Interval=1HOUR
Instantaneous Interval=1HOUR
Mapping Interval=1HOUR
Computation Time Step Use Courant=        0
Computation Time Step Use Time Series=    0
Computation Time Step Count To Double=0
Computation Time Step Max Doubling=0
Computation Time Step Max Halving=0
Computation Time Step Residence Courant=0
Run HTab= 0
Run UNet= 0
Run Sediment= 0
Run PostProcess= 0
Run WQNet= 0
Run RASMapper= 0
UNET Theta= 1
UNET Theta Warmup= 1
UNET ZTol= 0.02
UNET ZSATol= 0.02
UNET MxIter= 20
UNET Max Iter WO Improvement= 0
UNET MaxInSteps= 0
UNET DtIC= 0
UNET DtMin= 0
UNET MaxCRTS= 20
UNET WFStab= 2
UNET SFStab= 1
UNET WFX= 1
UNET SFX= 1
UNET 1D Methodology=Finite Difference
UNET DSS MLevel= 4
UNET Pardiso=0
UNET DZMax Abort= 100
UNET Use Existing IB Tables=-1
UNET Froude Reduction=False
UNET Froude Limit= 0.8
UNET Froude Power= 4
UNET D1 Cores= 0
UNET D2 Coriolis=0
UNET D2 Cores= 0
UNET D2 Theta= 1
UNET D2 Theta Warmup= 1
UNET D2 Z Tol= 0.01
UNET D2 Volume Tol= 0.01
UNET D2 Max Iterations= 20
UNET D2 Equation= 0
UNET D2 RampUpFraction=0.1
UNET D2 TimeSlices= 1
UNET D2 BCVolumeCheck=0
UNET D1D2 MaxIter= 0
UNET D1D2 ZTol=0.01
UNET D1D2 QTol=0.1
UNET D1D2 MinQTol=1
Write IC File= 0
Write IC File at Fixed DateTime=0
Write IC File at Sim End=0
Echo Input=False
Echo Parameters=False
Echo Output=False
Write Detailed= 0
HDF Write Warmup=0
HDF Write Time Slices=0
HDF Flush=0
HDF Face Node Velocities=0
HDF Compression= 1
HDF Chunk Size= 1
HDF Spatial Parts= 1
HDF Use Max Rows=0
HDF Fixed Rows= 1
Calibration Method= 0
Calibration Iterations= 20
Calibration Max Change=0.05
Calibration Tolerance=0.2
Calibration Maximum=1.5
Calibration Minimum=0.5
Calibration Optimization Method= 1
WQ AD Non Conservative
WQ ULTIMATE=-1
WQ Max Comp Step=1HOUR
WQ Output Interval=15MIN
WQ Output Selected Increments= 0
WQ Output face flow=0
WQ Output face velocity=0
WQ Output face area=0
WQ Output face dispersion=0
WQ Output cell volume=0
WQ Output cell surface area=0
WQ Output cell continuity=0
WQ Output cumulative cell continuity=0
WQ Output face conc=0
WQ Output face dconc_dx=0
WQ Output face courant=0
WQ Output face peclet=0
WQ Output face adv mass=0
WQ Output face disp mass=0
WQ Output cell mass=0
WQ Output cell source sink temp=0
WQ Output nsm pathways=0
WQ Output nsm derived pathways=0
WQ Output MaxMinRange=-1
WQ Daily Max Min Mean=-1
WQ Daily Range=0
WQ Daily Time=0
WQ Create Restart=0
WQ Fixed Restart=0
WQ System Summary=0
WQ Write To DSS=0
WQ Use Fixed Temperature=0
Sorting and Armoring Iterations= 10
XS Update Threshold= 0.02
Bed Roughness Predictor= 0
Hydraulics Update Threshold= 0.02
Energy Slope Method= 1
Volume Change Method= 1
Sediment Retention Method= 0
XS Weighting Method= 0
Number of US Weighted Cross Sections= 1
Number of DS Weighted Cross Sections= 1
Upstream XS Weight=0
Main XS Weight=1
Downstream XS Weight=0
Number of DS XS's Weighted with US Boundary= 1
Upstream Boundary Weight= 1
Weight of XSs Associated with US Boundary= 0
Number of US XS's Weighted with DS Boundary= 1
Downstream Boundary Weight= 0.5
Weight of XSs Associated with DS Boundary= 0.5
Percentile Method= 0
Sediment Output Level= 3
Mass or Volume Output= 0
Output Increment Type= 1
Profile and TS Output Increment= 1
XS Output Flag= 0
XS Output Increment= 10
Write Gradation File= 0
Read Gradation Hotstart= 0
Write HDF5 File= 1
Write Binary Output= 1
Write DSS Sediment File= 0
SV Curve= 0
Specific Gage Flag= 0

--- LAURELRN2.f01 (steady flow) ---

Flow Title=Flow
Program Version=5.07
Number of Profiles= 6
Profile Names=f1p,f10p,f4p,f2p,f02p,f1pplus
River Rch & RM=LAURELRN2,Main            ,16185
     488     256     342     413     684     722
River Rch & RM=LAURELRN2,Main            ,15475
     566     299     398     479     791     838
River Rch & RM=LAURELRN2,Main            ,13512
     655     348     462     555     913     969
River Rch & RM=LAURELRN2,Main            ,11607
     732     390     517     621    1020    1080
River Rch & RM=LAURELRN2,Main            ,8528
     852     457     604     724    1180    1260
River Rch & RM=LAURELRN2,Main            ,6084
     949     511     674     807    1310    1400
River Rch & RM=LAURELRN2,Main            ,2993
    1060     571     751     899    1460    1560
River Rch & RM=MEADOWCK1,Main            ,75581
     529     279     371     448     740     782
River Rch & RM=MEADOWCK1,Main            ,73978
     598     316     420     506     834     884
River Rch & RM=MEADOWCK1,Main            ,71430
     678     361     478     575     945    1000
River Rch & RM=MEADOWCK1,Main            ,69203
     792     424     560     672    1100    1170
River Rch & RM=MEADOWCK1,Main            ,67339
     882     474     625     749    1220    1300
River Rch & RM=MEADOWCK1,Main            ,64109
    1010     548     721     863    1400    1500
River Rch & RM=MEADOWCK1,Main            ,61239
    1140     619     812     971    1570    1690
River Rch & RM=MEADOWCK1,Main            ,59576
    1280     700     917    1090    1770    1900
River Rch & RM=MEADOWCK1,Main            ,56054
    1450     794    1040    1240    1990    2140
River Rch & RM=MEADOWCK1,Main            ,50980
    1720     950    1240    1470    2360    2550
River Rch & RM=MEADOWCK1,Main            ,44209
    1940    1080    1400    1660    2650    2870
River Rch & RM=MEADOWCK1,Main            ,42625
    1840    1020    1320    1570    2510    2720
River Rch & RM=MEADOWCK1,Main            ,38864
    2190    1220    1580    1870    2980    3230
River Rch & RM=MEADOWCK1,Main            ,31946
    2500    1400    1810    2140    3390    3690
River Rch & RM=MEADOWCK1,Main            ,24140
    2780    1560    2020    2390    3780    4120
River Rch & RM=MEADOWCK1,Main            ,14473
    3730    2120    2720    3210    5030    5510
River Rch & RM=MFANTNYCK,Main            ,62239
    1310     714     935    1120    1800    1940
River Rch & RM=MFANTNYCK,Main            ,61636
    1410     772    1010    1200    1940    2090
River Rch & RM=MFANTNYCK,Main            ,58106
    1580     868    1130    1350    2160    2330
River Rch & RM=MFANTNYCK,Main            ,55360
    1820    1010    1310    1560    2490    2690
River Rch & RM=MFANTNYCK,Main            ,52938
    2030    1120    1460    1730    2760    3000
River Rch & RM=MFANTNYCK,Main            ,48015
    2310    1290    1670    1980    3150    3420
River Rch & RM=MFANTNYCK,Main            ,44550
    2730    1530    1980    2340    3700    4030
River Rch & RM=MFANTNYCK,Main            ,38407
    3100    1750    2250    2660    4200    4590
River Rch & RM=MFANTNYCK,Main            ,29623
    3460    1960    2520    2980    4680    5120
River Rch & RM=MFANTNYCK,Main            ,25319
    3880    2210    2840    3340    5230    5740
River Rch & RM=MFANTNYCK,Main            ,16951
    4320    2470    3160    3720    5810    6390
River Rch & RM=MFANTNYCK,Main            ,12276
    4850    2780    3560    4180    6510    7170
River Rch & RM=NFANTNYCK,Main            ,44991
    1410     771    1010    1200    1940    2080
River Rch & RM=NFANTNYCK,Main            ,42260
    1650     907    1180    1410    2260    2440
River Rch & RM=NFANTNYCK,Main            ,38018
    1880    1040    1360    1610    2570    2790
River Rch & RM=NFANTNYCK,Main            ,34796
    2230    1240    1610    1910    3040    3300
River Rch & RM=NFANTNYCK,Main            ,29090
    2490    1390    1800    2140    3390    3680
River Rch & RM=NFANTNYCK,Main            ,20166
    2840    1590    2060    2430    3840    4190
River Rch & RM=NFANTNYCK,Main            ,11738
    3200    1810    2330    2750    4330    4740
River Rch & RM=NFANTNYCK,Main            ,8976
    3560    2020    2600    3060    4810    5270
River Rch & RM=TWOMILERN,Main            ,1186
     601     318     423     509     838     889
Boundary for River Rch & Prof#=LAURELRN2,Main            , 1
Up Type= 0
Dn Type= 3
Dn Slope=0.035124
Boundary for River Rch & Prof#=LAURELRN2,Main            , 2
Up Type= 0
Dn Type= 3
Dn Slope=0.035124
Boundary for River Rch & Prof#=LAURELRN2,Main            , 3
Up Type= 0
Dn Type= 3
Dn Slope=0.035124
Boundary for River Rch & Prof#=LAURELRN2,Main            , 4
Up Type= 0
Dn Type= 3
Dn Slope=0.035124
Boundary for River Rch & Prof#=LAURELRN2,Main            , 5
Up Type= 0
Dn Type= 3
Dn Slope=0.035124
Boundary for River Rch & Prof#=LAURELRN2,Main            , 6
Up Type= 0
Dn Type= 3
Dn Slope=0.035124
Boundary for River Rch & Prof#=MEADOWCK1,Main            , 1
Up Type= 0
Dn Type= 3
Dn Slope=0.011297
Boundary for River Rch & Prof#=MEADOWCK1,Main            , 2
Up Type= 0
Dn Type= 3
Dn Slope=0.011297
Boundary for River Rch & Prof#=MEADOWCK1,Main            , 3
Up Type= 0
Dn Type= 3
Dn Slope=0.011297
Boundary for River Rch & Prof#=MEADOWCK1,Main            , 4
Up Type= 0
Dn Type= 3
Dn Slope=0.011297
Boundary for River Rch & Prof#=MEADOWCK1,Main            , 5
Up Type= 0
Dn Type= 3
Dn Slope=0.011297
Boundary for River Rch & Prof#=MEADOWCK1,Main            , 6
Up Type= 0
Dn Type= 3
Dn Slope=0.011297
Boundary for River Rch & Prof#=MFANTNYCK,Main            , 1
Up Type= 0
Dn Type= 3
Dn Slope=0.001473
Boundary for River Rch & Prof#=MFANTNYCK,Main            , 2
Up Type= 0
Dn Type= 3
Dn Slope=0.001473
Boundary for River Rch & Prof#=MFANTNYCK,Main            , 3
Up Type= 0
Dn Type= 3
Dn Slope=0.001473
Boundary for River Rch & Prof#=MFANTNYCK,Main            , 4
Up Type= 0
Dn Type= 3
Dn Slope=0.001473
Boundary for River Rch & Prof#=MFANTNYCK,Main            , 5
Up Type= 0
Dn Type= 3
Dn Slope=0.001473
Boundary for River Rch & Prof#=MFANTNYCK,Main            , 6
Up Type= 0
Dn Type= 3
Dn Slope=0.001473
Boundary for River Rch & Prof#=NFANTNYCK,Main            , 1
Up Type= 0
Dn Type= 3
Dn Slope=0.006644
Boundary for River Rch & Prof#=NFANTNYCK,Main            , 2
Up Type= 0
Dn Type= 3
Dn Slope=0.006644
Boundary for River Rch & Prof#=NFANTNYCK,Main            , 3
Up Type= 0
Dn Type= 3
Dn Slope=0.006644
Boundary for River Rch & Prof#=NFANTNYCK,Main            , 4
Up Type= 0
Dn Type= 3
Dn Slope=0.006644
Boundary for River Rch & Prof#=NFANTNYCK,Main            , 5
Up Type= 0
Dn Type= 3
Dn Slope=0.006644
Boundary for River Rch & Prof#=NFANTNYCK,Main            , 6
Up Type= 0
Dn Type= 3
Dn Slope=0.006644
Boundary for River Rch & Prof#=TWOMILERN,Main            , 1
Up Type= 0
Dn Type= 3
Dn Slope=0.021324
Boundary for River Rch & Prof#=TWOMILERN,Main            , 2
Up Type= 0
Dn Type= 3
Dn Slope=0.021324
Boundary for River Rch & Prof#=TWOMILERN,Main            , 3
Up Type= 0
Dn Type= 3
Dn Slope=0.021324
Boundary for River Rch & Prof#=TWOMILERN,Main            , 4
Up Type= 0
Dn Type= 3
Dn Slope=0.021324
Boundary for River Rch & Prof#=TWOMILERN,Main            , 5
Up Type= 0
Dn Type= 3
Dn Slope=0.021324
Boundary for River Rch & Prof#=TWOMILERN,Main            , 6
Up Type= 0
Dn Type= 3
Dn Slope=0.021324
DSS Import GetInterval= 0
DSS Import GetPeak= 0
DSS Import FillOption= 0

--- LAURELRN2.g01 (geometry) ---

Geom Title=Geometry
Program Version=5.07

River Reach=LAURELRN2       ,Main
Reach XY= 30
2222168.70977272332666.7044799772222382.14635372333332.119815812
 2223122.8007123333843.0318517242223176.36819047 334506.91405414
 2223685.4314768334806.3455418942224382.72371739336391.834168807
 2224626.6185708336456.3251815592224489.25532848336536.783353984
2224738.17641856336849.128529817 2224743.6813288337036.190491647
2225214.73812947337308.9402742242225574.43852556337698.480505645
2225542.34377347338055.8879273092225774.38596031338275.711634651
2225837.57251371338741.6027632212226036.26995097338708.414509401
2226110.56409372338975.2601043132226641.28252047339169.911945984
2226556.73085231339596.7755935642226676.42287014339852.947653398
 2227303.3356583340077.0886093082227278.19692905340730.421948314
2227541.11339797341115.4221625632227115.28026013 341905.00555715
2227750.39677206342184.4347883162227863.72298898342354.813712642
2227853.79453114342825.3879027222227585.48109138343024.953448474
2227663.07575247343195.2556013172227573.54837248343910.161651805

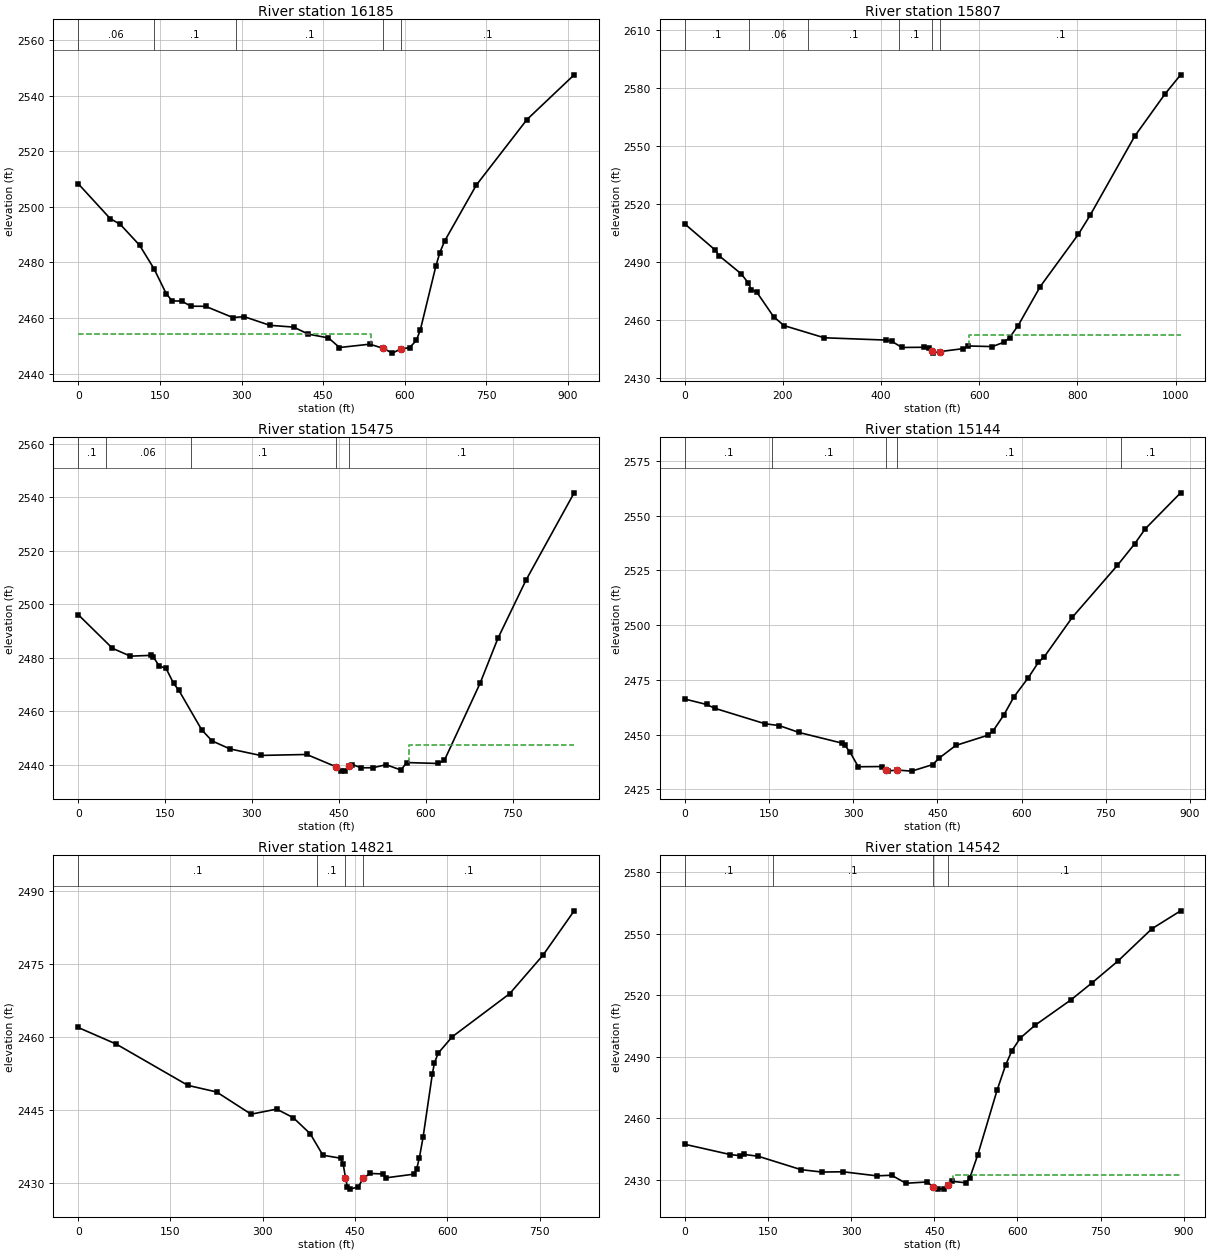
Type RM Length L Ch R = 1 ,16185   ,374.5,378,380.5
XS GIS Cut Line= 4
2221634.37849231332820.9630297272221997.22553563332734.157429054
2222137.85058247332702.0393830542222485.07298514332516.275318891
#Sta/Elev= 30
       0 2508.37    58.6 2495.84    77.3 2493.72   112.7 2486.24   139.5 2477.66
   161.6  2468.8   172.5 2466.18   190.1 2466.08     207 2464.26     234 2464.21
   284.1 2460.17   304.8 2460.49   352.1 2457.37   395.9 2456.72   422.8 2454.18
   459.8 2452.83     480 2449.37   535.6 2450.57   560.62449.068   577.1 2447.35
  592.192448.819   608.7 2449.34   621.2 2451.91   628.6 2455.78   657.1 2478.72
   664.4 2483.59   673.3 2487.78   731.3 2507.86   824.4 2531.49   911.1  2547.6
#Mann= 5 ,-1 , 0
       0     .06       0   139.5      .1       0  289.37      .1       0
   560.6    .045       0  592.19      .1       0
#XS Ineff= 2 , 0
          537.07 2454.32
Permanent Ineff=
       F       F
Bank Sta=560.6,592.19
XS Rating Curve= 0 ,0
Exp/Cntr=0.3,0.1

Type RM Length L Ch R = 1 ,15807   ,334.3,331.7,325.7
XS GIS Cut Line= 2
2221727.08368747333166.6522989722222679.34064122332828.978433639
#Sta/Elev= 30
       0 2509.72    62.7 2496.03      70 2493.22   115.2 2483.81   129.2 2479.23
   136.1 2475.52   146.6 2474.43   181.1 2461.64   202.3 2457.02   284.4  2450.7
   409.9 2449.51   421.6 2448.92   442.5 2445.68   487.7 2445.78   498.2 2445.35
  503.232443.598   505.1 2442.75  520.842443.567   567.8 2445.09   578.2 2446.45
     627 2446.14   651.3 2448.49   661.8 2450.76   679.2 2456.96   724.4 2477.23
   802.2 2504.34   826.2 2514.23   916.7 2555.04   978.5 2576.94  1010.4  2586.9
#Mann= 6 ,-1 , 0
       0      .1       0  131.93     .06       0  251.91      .1       0
  435.73      .1       0  503.23    .045       0  520.84      .1       0
#XS Ineff= 2 , 0
                          579.97         2452.06
Permanent Ineff=
       F       F
Bank Sta=503.23,520.84
XS Rating Curve= 0 ,0
Exp/Cntr=0.3,0.1

Type RM Length L Ch R = 1 ,15475   ,328.4,331.8,322.9
XS GIS Cut Line= 2
2222024.56636022333563.7443525642222662.06606947332991.869183972
#Sta/Elev= 30
       0 2496.07    59.2 2483.47    90.1 2480.54   125.1 2480.83   129.8 2480.22
   139.6 2476.92   151.8 2475.93   164.6 2470.39   173.9 2467.71   213.3 2452.97
   231.1 2448.84     262 2445.84   314.8  2443.4   394.6 2443.76  444.732439.203
   454.1 2437.53   460.3 2437.71  467.432439.315   473.6 2439.99   488.5 2438.78
   508.5 2438.79   531.7 2439.93   557.3 2437.94   567.1 2440.74   621.1 2440.39
   632.2 2441.51   693.9 2470.37   724.7 2487.18   773.3    2509   856.4 2541.64
#Mann= 5 ,-1 , 0
       0      .1       0   47.69     .06       0  194.31      .1       0
  444.73    .045       0  467.43      .1       0
#XS Ineff= 2 , 0
                          571.02         2447.44
Permanent Ineff=
       F       F
Bank Sta=444.73,467.43
XS Rating Curve= 0 ,0
Exp/Cntr=0.3,0.1

Type RM Length L Ch R = 1 ,15144   ,319.4,322.8,312.1
XS GIS Cut Line= 4
2222279.77451122333710.6190588182222472.48278722333528.327428639
2222675.60770905333263.7442963872222869.35797772333055.410723567
#Sta/Elev= 30
       0 2466.25    39.1 2463.75    53.4 2462.03   143.5 2454.92     168 2454.14
   203.8 2450.96   280.3  2446.1   285.2 2445.15   294.6 2441.92   309.2 2435.31
   350.6 2435.41  358.142434.028   362.4  2433.4  378.492433.796   404.3 2433.31
   441.6 2436.28   453.3 2439.27   482.9 2445.05   540.3 2449.73   549.1 2451.62
   568.4 2458.94   586.3 2467.18   612.2 2476.04   630.1 2483.06   640.6 2485.59
   690.4 2503.57   770.6 2527.26   801.2 2537.05   820.4 2544.01   883.3 2560.43
#Mann= 5 ,-1 , 0
       0      .1       0  156.12      .1       0  358.14    .045       0
  378.49      .1       0  777.69      .1       0
Bank Sta=358.14,378.49
XS Rating Curve= 0 ,0
Exp/Cntr=0.3,0.1

Type RM Length L Ch R = 1 ,14821   ,274.1,279.3,282.7
XS GIS Cut Line= 3
2222375.00037064333889.785695225 2222657.2918008333662.702487975
2222926.04191947333309.577538058
#Sta/Elev= 30
       0 2461.92    61.6 2458.53   178.3 2450.04     225 2448.68     281 2444.12
   322.6 2445.17   349.6  2443.4   377.1 2440.11   397.7  2435.7   426.5 2435.09
   430.6 2433.97  434.412431.062   437.6 2429.18   442.3 2428.74   455.4 2429.22
   463.3 2431.02     475 2431.96   495.4 2431.85   500.7 2431.07   546.1 2431.82
     550 2432.83   554.6 2435.22   560.5 2439.36   575.7 2452.46   579.1 2454.68
   585.1 2456.65   607.9 2460.01   701.3 2468.86   755.5 2476.77   806.1 2485.87
#Mann= 4 ,-1 , 0
       0      .1       0  388.82      .1       0  434.41    .045       0
   463.3      .1       0
Bank Sta=434.41,463.3
XS Rating Curve= 0 ,0
Exp/Cntr=0.3,0.1

Type RM Length L Ch R = 1 ,14542   ,269.9,270.2,261.5
XS GIS Cut Line= 2
2222534.37537996333937.7025941462223305.20848396333484.577516139
#Sta/Elev= 30
       0 2447.33    82.6 2442.29    99.1 2441.79   106.7  2442.4   132.9 2441.46
   209.8 2434.95   247.5 2433.78   285.6 2433.92   346.5 2431.93   373.1 2432.23
   398.9 2428.32   437.3 2428.96  447.59 2426.57   456.5 2425.46   468.3 2425.67
  474.922427.542   482.8 2429.23   506.8 2428.56   513.8 2430.69   528.4 2442.12
   563.4 2473.78   578.6  2485.9   590.1    2493   605.3 2499.16   631.4 2505.27
   696.1 2517.66   734.7 2526.07   781.6 2536.75   842.3 2552.36   894.2 2561.13
#Mann= 4 ,-1 , 0
       0      .1       0  159.94      .1       0  447.59    .045       0
  474.92      .1       0
#XS Ineff= 2 , 0
                          483.31         2432.46
Permanent Ineff=
       F       F
Bank Sta=447.59,474.92
XS Rating Curve= 0 ,0
Exp/Cntr=0.3,0.1

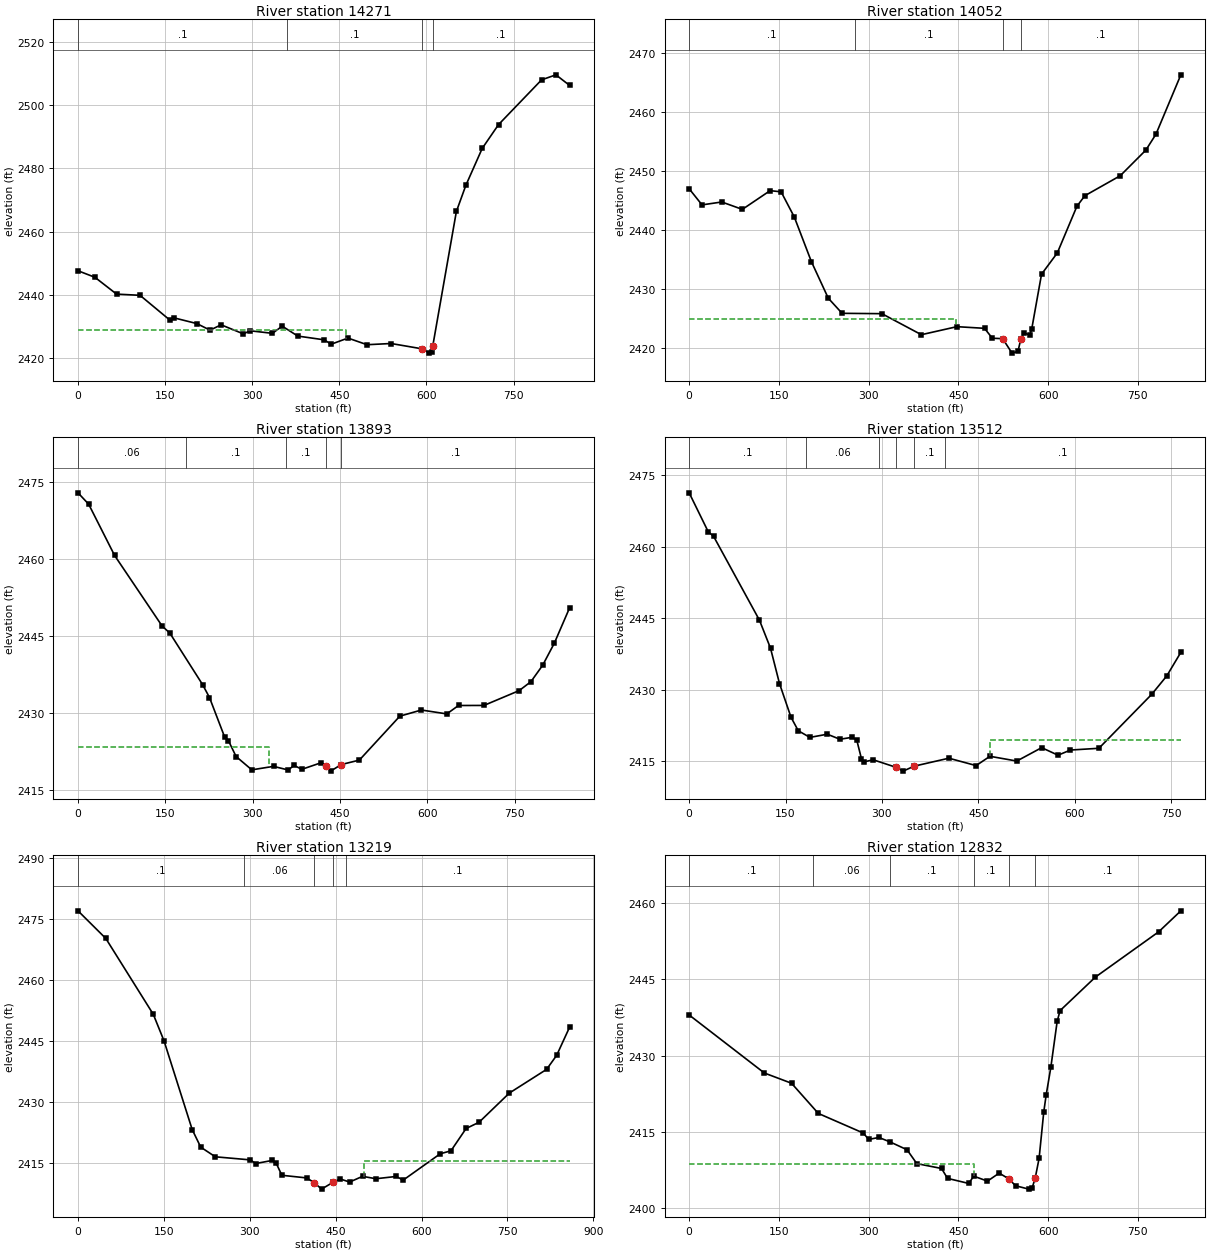
Type RM Length L Ch R = 1 ,14271   ,211.8,219.4,224.1
XS GIS Cut Line= 3
2222618.75021122334172.077453479 2222923.9585903333987.702494144
2223314.58346522333691.869096309
#Sta/Elev= 30
       0 2447.65    29.1 2445.59    66.4 2440.27   106.8 2439.89   157.6 2432.15
   166.1 2432.73   204.4 2430.97   227.4 2428.88   246.4 2430.57   284.7 2427.71
   296.4 2428.68   334.7 2427.88   351.7 2430.14   378.4 2427.01   423.7 2425.83
     436 2424.44   464.8 2426.38   497.7 2424.28   539.1 2424.66   592.82422.967
   604.6 2421.62   608.9 2421.98  610.772423.776   651.5 2466.38   667.9 2474.68
     696 2486.32   724.1 2493.84   798.2 2507.98   822.9 2509.57   846.6 2506.21
#Mann= 4 ,-1 , 0
       0      .1       0  360.54      .1       0   592.8    .045       0
  610.77      .1       0
#XS Ineff= 2 , 0
           461.8 2428.79
Permanent Ineff=
       F       F
Bank Sta=592.8,610.77
XS Rating Curve= 0 ,0
Exp/Cntr=0.3,0.1

Type RM Length L Ch R = 1 ,14052   ,156.1,159,160.5
XS GIS Cut Line= 4
2222653.12514247334192.9107451442222810.41682264334113.744236812
2222956.25019239334061.661007643 2223445.8335308334028.327412888
#Sta/Elev= 30
       0 2446.93    21.5  2444.2    54.5 2444.69    88.9 2443.44   135.3 2446.61
   153.7 2446.41   175.8 2442.13   204.2 2434.61   232.5  2428.4   255.6 2425.84
   322.1 2425.78   388.1 2422.22   447.5 2423.58   493.6  2423.3   506.7 2421.62
  523.962421.549   539.6  2419.1   549.5 2419.39   554.2 2421.44   559.4 2422.55
   569.2 2422.15   572.5 2423.17   588.9 2432.46   615.3 2436.07   648.1 2443.98
   661.3 2445.75   720.5 2449.14   763.2 2453.47   780.1 2456.16   821.7 2466.22
#Mann= 4 ,-1 , 0
       0      .1       0  277.52      .1       0  523.96    .045       0
   554.2      .1       0
#XS Ineff= 2 , 0
          446.52 2424.85
Permanent Ineff=
       F       F
Bank Sta=523.96,554.2
XS Rating Curve= 0 ,0
Exp/Cntr=0.3,0.1

Type RM Length L Ch R = 1 ,13893   ,382.9,380.8,360.3
XS GIS Cut Line= 5
 2222740.1558083334293.3596912322222975.57233222334220.443170398
2223115.15571447334198.5678860552223269.32240088334214.192854807
2223564.11413413334148.567986056
#Sta/Elev= 30
       0  2472.9    18.3 2470.69    62.9 2460.69   144.6 2446.93   157.7 2445.58
   214.1 2435.52   225.9 2433.01   251.7 2425.38   258.4 2424.61   271.6 2421.52
   298.6 2418.92   335.9  2419.6   361.2 2418.89   371.2 2419.79   384.5 2419.02
   417.5  2420.3  426.482419.668     434 2418.67   452.32419.951   483.4 2420.82
   552.9 2429.38   589.9 2430.58   633.6 2429.82   653.7 2431.46   697.4 2431.47
   757.9 2434.36   778.1  2436.1   798.3  2439.3   818.4 2443.62   844.7 2450.53
#Mann= 5 ,-1 , 0
       0     .06       0     186      .1       0  357.19      .1       0
  426.48    .045       0   452.3      .1       0
#XS Ineff= 2 , 0
          328.24 2423.28
Permanent Ineff=
       F       F
Bank Sta=426.48,452.3
XS Rating Curve= 0 ,0
Exp/Cntr=0.3,0.1

Type RM Length L Ch R = 1 ,13512   ,287.9,293.3,286.7
XS GIS Cut Line= 2
2222867.18770647334628.327525228 2223556.4238608334295.862310886
#Sta/Elev= 30
       0 2471.28    29.5 2463.17    38.1 2462.14   109.4 2444.58   126.6 2438.71
   140.6 2431.29   158.5 2424.23   169.8  2421.4   187.9    2420     215 2420.67
   234.7 2419.61   253.5 2420.02   260.8 2419.47   268.1 2415.55   271.7 2414.85
   286.4 2415.31  321.35 2413.76     333 2412.93  349.912413.962   404.2 2415.64
   446.6 2414.09   468.1 2416.04   509.9 2415.04   548.6 2417.85   574.1 2416.27
   593.4 2417.35   637.7 2417.72   719.8 2429.02   743.3 2432.89   765.2 2437.83
#Mann= 6 ,-1 , 0
       0      .1       0  181.68     .06       0  295.25      .1       0
  321.35    .045       0  349.91      .1       0  398.86      .1       0
#XS Ineff= 2 , 0
                          468.14          2419.5
Permanent Ineff=
       F       F
Bank Sta=321.35,349.91
XS Rating Curve= 0 ,0
Exp/Cntr=0.3,0.1

Type RM Length L Ch R = 1 ,13219   ,377.7,387,382.7
XS GIS Cut Line= 2
2222977.77803648334858.0150579812223725.57247263334436.068067223
#Sta/Elev= 30
       0 2476.98    48.6 2470.17   131.5 2451.49   150.3 2444.93   199.4 2423.12
   214.3 2418.79   239.8 2416.41     301 2415.65   310.2 2414.75   338.6  2415.5
   346.2  2414.8     356 2411.86   399.3 2411.21  412.932410.011   425.3 2408.45
   445.72410.167     458 2410.95   474.3 2410.19   496.9  2411.6   520.2 2411.01
   555.8 2411.57   567.9 2410.67   632.5 2417.15   651.3 2417.89   677.7 2423.38
   700.3 2424.91   753.3 2432.11   818.3 2437.94   835.9  2441.4   858.6 2448.38
#Mann= 5 ,-1 , 0
       0      .1       0   290.5     .06       0  412.93    .045       0
   445.7      .1       0  468.34      .1       0
#XS Ineff= 2 , 0
                          499.72         2415.28
Permanent Ineff=
       F       F
Bank Sta=412.93,445.7
XS Rating Curve= 0 ,0
Exp/Cntr=0.3,0.1

Type RM Length L Ch R = 1 ,12832   ,327.9,337.9,338.6
XS GIS Cut Line= 3
 2223218.2808363335124.6096691492223544.32250705334893.359803557
2223897.44745697334662.109609887
#Sta/Elev= 30
       0 2437.97   125.7 2426.57   171.1 2424.56   215.9 2418.63   291.2 2414.77
     300 2413.52   317.1 2413.91   335.9 2413.03   364.2 2411.49   380.5 2408.77
   421.8 2407.82   431.9 2405.87   467.2 2404.88   475.7 2406.31   498.6 2405.33
   518.2 2406.91  533.882405.803   545.7 2404.42   567.7 2403.76   573.1 2403.94
  578.312405.877   584.9  2409.8   592.7 2418.92   596.6 2422.17   604.5 2427.67
   615.1 2436.71   619.9 2438.82   679.1 2445.42   784.9 2454.32   821.8 2458.43
#Mann= 6 ,-1 , 0
       0      .1       0  207.79     .06       0   335.9      .1       0
  475.84      .1       0  533.88    .045       0  578.31      .1       0
#XS Ineff= 2 , 0
          475.38 2408.74
Permanent Ineff=
       F       F
Bank Sta=533.88,578.31
XS Rating Curve= 0 ,0
Exp/Cntr=0.3,0.1

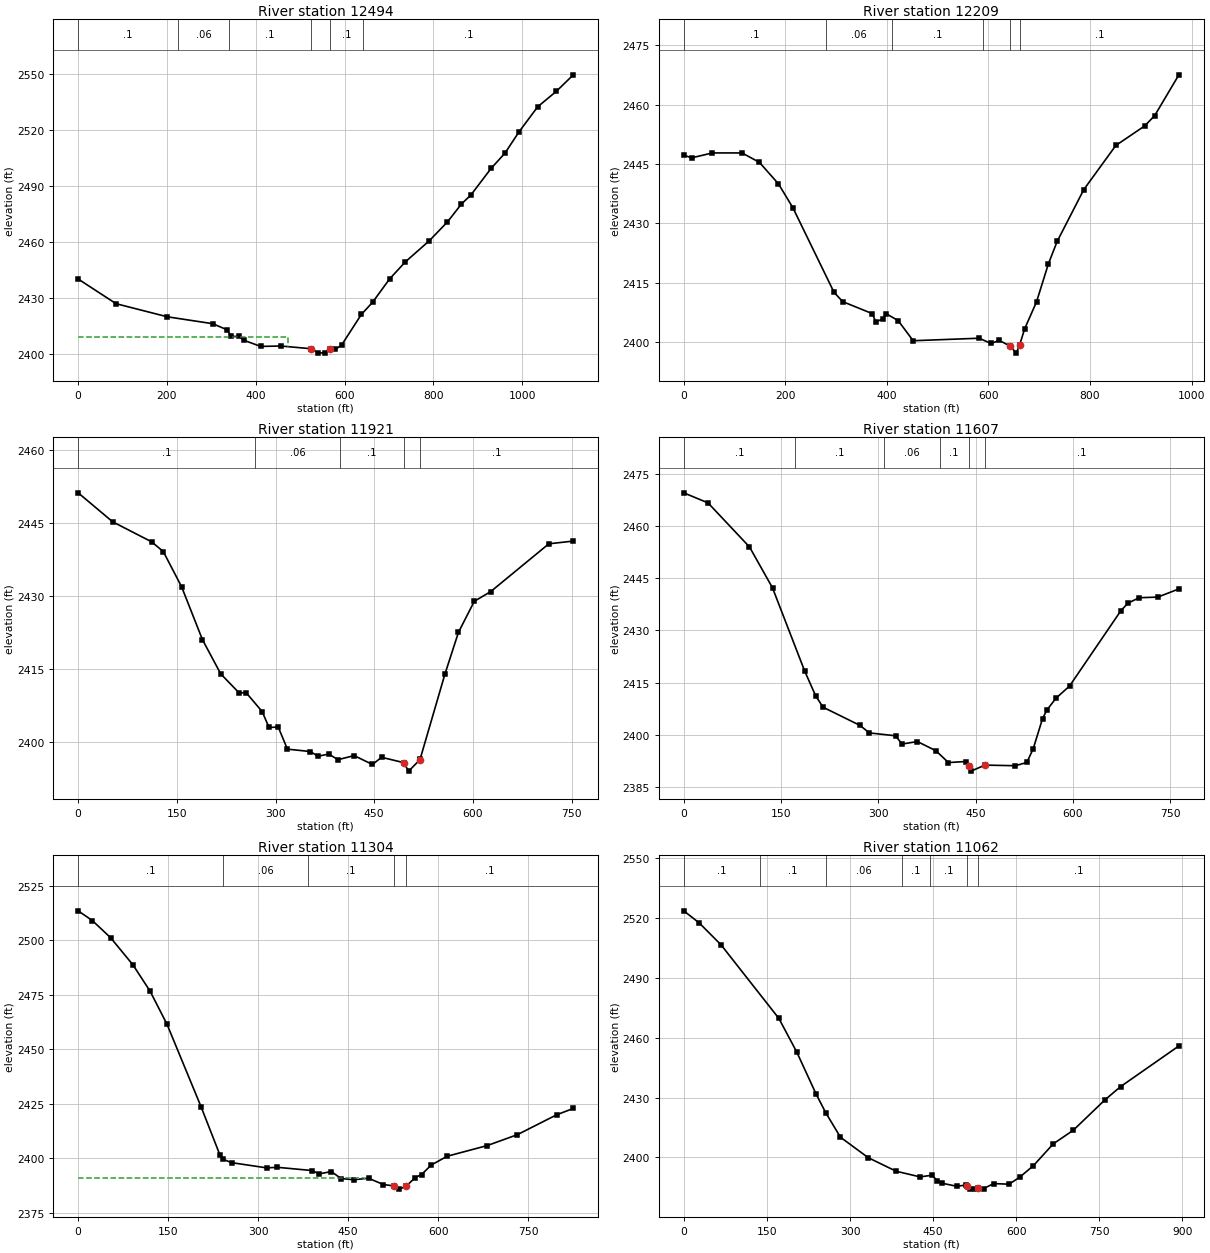
Type RM Length L Ch R = 1 ,12494   ,281.5,284.4,277.3
XS GIS Cut Line= 2
2223284.62880072335301.3747355642224328.69725063 334908.98477231
#Sta/Elev= 30
       0 2440.23    85.4 2426.99   201.1 2419.95   302.7 2416.28   334.8 2413.07
     345 2409.45   362.3 2409.42   373.5 2407.34   411.2 2404.08   456.9 2404.28
  524.88 2402.83     541 2400.47   555.1 2400.73  567.53 2402.53   579.6 2402.49
   593.6 2404.86   637.9 2421.21   663.4 2427.81   701.6  2440.3   737.3  2449.5
   790.8 2460.72   831.9 2470.88   863.5 2480.53   884.5 2485.26   930.1 2499.56
   961.5  2507.8   993.2 2519.25  1035.3 2532.69  1077.3 2540.98  1115.4 2549.81
#Mann= 6 ,-1 , 0
       0      .1       0  224.87     .06       0  339.21      .1       0
  524.88    .045       0  567.53      .1       0  642.37      .1       0
#XS Ineff= 2 , 0
          471.99 2409.25
Permanent Ineff=
       F       F
Bank Sta=524.88,567.53
XS Rating Curve= 0 ,0
Exp/Cntr=0.3,0.1

Type RM Length L Ch R = 1 ,12209   ,288.2,288.3,284.1
XS GIS Cut Line= 3
2223323.48895922335472.5262961392223716.19749139335356.901199311
2224274.53069231335267.318045139
#Sta/Elev= 30
       0 2447.24    15.5 2446.56    56.5  2447.8   114.7  2447.8   148.9 2445.43
   186.5 2439.99   214.8 2433.99   295.9 2412.62     313 2410.27   371.2 2407.25
     378 2405.19   391.7 2405.86   398.5 2407.23   422.1  2405.5   451.7 2400.41
   581.6 2401.04   604.8 2399.73   621.5 2400.49  643.122398.998   654.7 2397.28
   661.3 2399.34   671.3 2403.44   694.6 2410.22     718 2419.83   735.2 2425.46
   787.6 2438.54   850.7 2449.68   907.5 2454.61   927.2 2457.21   974.9 2467.51
#Mann= 6 ,-1 , 0
       0      .1       0   279.9     .06       0   409.5      .1       0
  590.04      .1       0  643.12    .045       0   661.3      .1       0
Bank Sta=643.12,661.3
XS Rating Curve= 0 ,0
Exp/Cntr=0.3,0.1

Type RM Length L Ch R = 1 ,11921   ,314.8,314.5,311.6
XS GIS Cut Line= 3
2223554.73915289335716.2764648052223981.82228822335560.026449233
2224266.19737564335471.484631553
#Sta/Elev= 30
       0 2451.16    52.5  2445.2   111.9 2441.08   129.4 2439.09   157.2 2431.87
   188.8 2421.03   216.7 2413.97   244.7 2410.06   255.2 2410.13   279.6 2406.24
   290.1 2402.97   304.1 2403.05     318 2398.52     353 2398.02   364.6 2397.06
   380.9 2397.51   394.9 2396.35   419.4 2397.19   447.3 2395.37   461.2 2396.84
   494.6 2395.75   502.4    2394   519.6 2396.37   519.6 2396.39   557.4  2413.9
     578  2422.5   602.1 2428.88   627.1 2430.88   715.4 2440.69   752.6 2441.25
#Mann= 5 ,-1 , 0
       0      .1       0  269.22     .06       0   398.2      .1       0
   494.6    .045       0   519.6      .1       0
Bank Sta=494.6,519.6
XS Rating Curve= 0 ,0
Exp/Cntr=0.3,0.1

Type RM Length L Ch R = 1 ,11607   ,300.7,302.6,298
XS GIS Cut Line= 4
2223677.65557373336011.1548120682224072.70760514335848.477643982
2224113.12451905335832.2276764812224390.42777023335738.003127396
#Sta/Elev= 30
       0 2469.53    37.5 2466.63   101.4 2453.99   136.9 2442.24   186.5 2418.36
   203.5 2411.22   214.9 2407.97   271.7 2402.76   286.4 2400.59   326.6 2399.77
   336.7  2397.4   360.4 2398.11   388.8 2395.49   408.3 2392.08   434.9 2392.38
  439.682391.148   443.1 2389.62  464.572391.351   511.4 2391.17   529.2 2392.11
     539 2396.05   553.4 2404.71   560.3 2407.22   574.2 2410.57     595 2414.04
   674.3  2435.7   685.1 2437.84   702.4 2439.41   731.2 2439.59   763.7 2441.94
#Mann= 6 ,-1 , 0
       0      .1       0     172      .1       0  308.55     .06       0
  394.68      .1       0  439.68    .045       0  464.57      .1       0
Bank Sta=439.68,464.57
XS Rating Curve= 0 ,0
Exp/Cntr=0.3,0.1

Type RM Length L Ch R = 1 ,11304   ,242.3,242.3,241.6
XS GIS Cut Line= 2
2223778.40504414336231.406011984 2224544.0301533335923.072639138
#Sta/Elev= 30
       0 2513.45    23.7 2508.97    53.9 2501.18    91.5 2488.62   119.8 2476.67
   148.1 2461.46   204.7 2423.77   236.5 2401.44   241.7 2399.59   255.6 2398.06
   314.3 2395.66     332 2395.92   389.3 2394.45   401.9 2392.92   422.1 2393.97
   438.1 2390.78   459.3 2390.25   484.1  2390.9   508.8 2388.03  526.342387.377
   535.5 2385.92  546.392387.197   561.9  2391.2   572.5 2392.62   588.5 2396.94
   614.9 2400.97   681.8 2405.87   732.2 2410.88   797.8    2420   825.4  2422.9
#Mann= 5 ,-1 , 0
       0      .1       0   242.2     .06       0  383.92      .1       0
  526.34    .045       0  546.39      .1       0
#XS Ineff= 2 , 0
          478.01 2391.03
Permanent Ineff=
       F       F
Bank Sta=526.34,546.39
XS Rating Curve= 0 ,0
Exp/Cntr=0.3,0.1

Type RM Length L Ch R = 1 ,11062   ,348.6,351.3,347.2
XS GIS Cut Line= 2
2223883.61349514336466.8225358872224700.28016889336104.322604731
#Sta/Elev= 30
       0 2523.54      28 2517.46    67.5 2506.44   171.6 2469.66   203.9 2452.82
   238.8 2431.78   256.2 2422.42   282.8 2410.13   333.1 2399.86   383.3  2393.1
   426.4 2390.27     448  2391.1   457.6 2388.34   465.9 2387.11   492.4 2385.58
     509 2386.16  511.422385.486   516.2 2384.35   524.7 2384.14  531.722384.506
   541.3 2384.44   559.2 2386.92   586.9 2386.61   605.9 2390.03     631  2395.9
   666.9 2406.84   702.8  2413.6   760.2 2428.89   788.3 2435.49   893.5 2455.86
#Mann= 7 ,-1 , 0
       0      .1       0  137.07      .1       0  256.77     .06       0
  393.94      .1       0  444.55      .1       0  511.42    .045       0
  531.72      .1       0
Bank Sta=511.42,531.72
XS Rating Curve= 0 ,0
Exp/Cntr=0.3,0.1

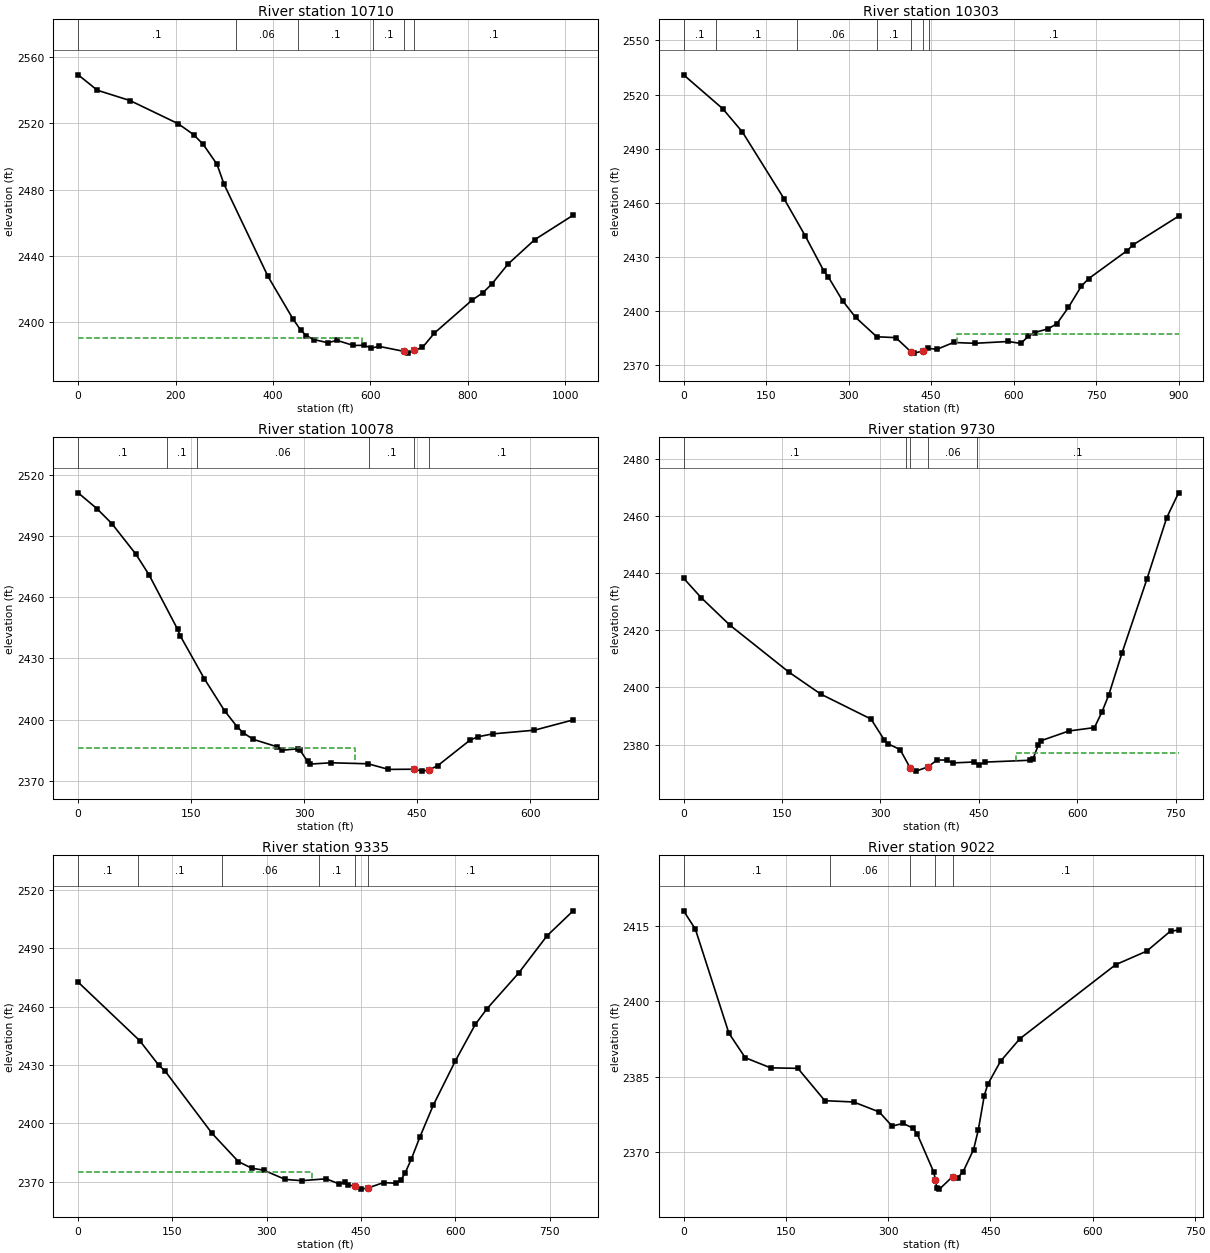
Type RM Length L Ch R = 1 ,10710   ,405.4,407.2,401.6
XS GIS Cut Line= 3
2223956.53001598336718.906021222 2224512.7802158 336418.90596506
2224855.48851989336244.947651565
#Sta/Elev= 30
       0 2549.29    39.4 2539.98   106.5 2533.75   205.1 2519.81     237 2513.18
   256.5 2507.37     285  2495.3   299.5 2483.22   389.8 2427.52   440.6  2402.1
   456.9 2395.11   468.1 2391.86   483.5 2389.44   512.8 2387.52   531.4 2388.95
     565 2385.88   587.4 2385.95   602.2 2384.25   617.2 2385.35  668.722382.309
   677.6 2381.24  690.532382.993   706.9 2384.66   731.4 2393.35   808.7 2413.24
   830.8 2417.67   849.2 2422.93   882.6 2435.02   937.5 2449.78  1016.3 2464.53
#Mann= 6 ,-1 , 0
       0      .1       0  323.55     .06       0  450.62      .1       0
  605.43      .1       0  668.72    .045       0  690.53      .1       0
#XS Ineff= 2 , 0
             582 2390.18
Permanent Ineff=
       F       F
Bank Sta=668.72,690.53
XS Rating Curve= 0 ,0
Exp/Cntr=0.3,0.1

Type RM Length L Ch R = 1 ,10303   ,222.3,225.6,227.1
XS GIS Cut Line= 4
2224172.15524089336849.1144222322224470.07163981336672.031114981
2224575.28009081336605.3642535662224920.07172406336351.197767138
#Sta/Elev= 30
       0 2530.94      71 2512.18   106.9 2499.23   182.6 2462.18   220.8 2441.74
   255.1 2421.97   262.8 2418.92   288.8 2405.68   312.7 2396.37     351 2385.64
   385.6 2385.17   413.42377.237   419.1 2376.57  434.292377.703   443.8 2379.25
   460.4 2378.68   490.5 2382.47   529.2 2382.02     590 2383.02     613 2381.95
   625.9 2385.82   638.1 2387.99   662.6 2390.08   678.5 2392.95   699.3 2401.95
   722.7 2413.68     736 2417.88   805.7 2433.36   817.5 2436.77   899.5 2452.55
#Mann= 7 ,-1 , 0
       0      .1       0   58.14      .1       0  206.37     .06       0
  351.01      .1       0   413.4    .045       0  434.29      .1       0
  445.92      .1       0
#XS Ineff= 2 , 0
                          496.32         2387.14
Permanent Ineff=
       F       F
Bank Sta=413.4,434.29
XS Rating Curve= 0 ,0
Exp/Cntr=0.3,0.1

Type RM Length L Ch R = 1 ,10078   ,349.7,347.7,340.6
XS GIS Cut Line= 2
2224262.78005964336922.0309430662224886.73845738336715.781027481
#Sta/Elev= 30
       0  2511.1      25 2503.32    44.8 2495.99    76.8 2480.98    94.1 2470.94
   132.1 2444.21   135.5 2441.09   167.5 2420.05   194.3  2404.4     211 2396.56
   218.8 2393.68   232.3 2390.38   263.4 2386.81   270.3    2385   291.5 2385.74
   294.5 2385.09   304.5 2379.59   308.3 2378.26   335.7 2378.89     385 2378.39
     412 2375.65  446.042375.736   456.9  2374.8  466.312375.455   477.6 2377.54
   520.1 2389.94   530.4 2391.59   550.2 2393.03   605.8 2394.85   657.2 2399.89
#Mann= 6 ,-1 , 0
       0      .1       0  117.85      .1       0  157.82     .06       0
  386.68      .1       0  446.04    .045       0  466.31      .1       0
#XS Ineff= 2 , 0
          367.23 2385.93
Permanent Ineff=
       F       F
Bank Sta=446.04,466.31
XS Rating Curve= 0 ,0
Exp/Cntr=0.3,0.1

Type RM Length L Ch R = 1 ,9730    ,394.7,395.2,388.6
XS GIS Cut Line= 3
 2224506.5302283 337290.780861722224838.82188655337054.322673231
2225117.98832297336849.114422232
#Sta/Elev= 30
       0 2438.21    26.7 2431.43    70.3 2421.85   160.8 2405.31   209.1 2397.67
   285.6 2388.95   305.8 2381.67   311.4 2380.31   329.9 2378.28  345.362371.834
   354.1 2370.74  371.952372.185   386.3 2374.62   400.8 2374.62   409.8  2373.6
   443.1 2373.94   450.1 2372.99   459.5  2373.9   528.6 2374.55   532.2 2374.91
   540.8 2379.97   544.8 2381.39     587 2384.77   626.1 2385.97   637.8 2391.58
     648 2397.45   668.3 2412.22   705.9  2437.8   736.2 2459.36   754.3 2468.07
#Mann= 5 ,-1 , 0
       0      .1       0  338.87     .06       0  345.36    .045       0
  371.95     .06       0  447.64      .1       0
#XS Ineff= 2 , 0
                          506.62         2377.19
Permanent Ineff=
       F       F
Bank Sta=345.36,371.95
XS Rating Curve= 0 ,0
Exp/Cntr=0.3,0.1

Type RM Length L Ch R = 1 ,9335    ,311.2,313,312.7
XS GIS Cut Line= 2
2224778.40501264337547.0310053972225374.23846664337032.447716981
#Sta/Elev= 30
       0 2472.53      98 2442.42   128.1 2429.87   138.2 2426.86     213 2394.79
   254.9 2380.29   275.9 2376.92   295.1 2375.87   329.4 2371.14   355.7 2370.49
   394.5 2371.46   414.2 2368.92   424.7 2369.65   429.4 2368.19  440.012367.835
   450.3 2366.15  460.392366.711   485.8  2369.5   506.1 2369.18   513.1 2370.66
   520.1 2374.52   529.7 2381.42   543.4 2392.87   564.8 2409.28     600  2432.1
   631.7 2450.84   650.4 2458.92   700.4 2477.12   745.7 2496.34   787.3 2509.19
#Mann= 6 ,-1 , 0
       0      .1       0   95.16      .1       0  228.08     .06       0
  382.32      .1       0  440.01    .045       0  460.39      .1       0
#XS Ineff= 2 , 0
          371.25 2374.87
Permanent Ineff=
       F       F
Bank Sta=440.01,460.39
XS Rating Curve= 0 ,0
Exp/Cntr=0.3,0.1

Type RM Length L Ch R = 1 ,9022    ,171.7,173.2,172
XS GIS Cut Line= 4
2225010.69687089337695.9893689012225280.48832606337499.114434555
2225344.03019372337451.1975356492225584.65504055337252.239272147
#Sta/Elev= 30
       0 2418.05    17.3 2414.39    66.4 2393.68    90.4 2388.79   127.6 2386.77
   167.6 2386.67   207.1 2380.23   249.3 2379.97   286.9 2377.98   305.7 2375.16
   321.9 2375.71   336.2 2374.76   342.3 2373.67     367 2365.93   369.2 2364.46
   371.3 2362.82   375.2 2362.61  394.472365.115   401.8 2364.88   409.8 2366.06
   425.2  2370.5   432.2 2374.44   440.9 2381.24   446.1 2383.52   464.8  2388.1
     493 2392.56   633.5 2407.32   679.2 2410.03   714.1 2414.03   725.8 2414.18
#Mann= 5 ,-1 , 0
       0      .1       0  214.91     .06       0  332.19      .1       0
   369.2    .045       0  394.47      .1       0
Bank Sta=369.2,394.47
XS Rating Curve= 0 ,0
Exp/Cntr=0.3,0.1