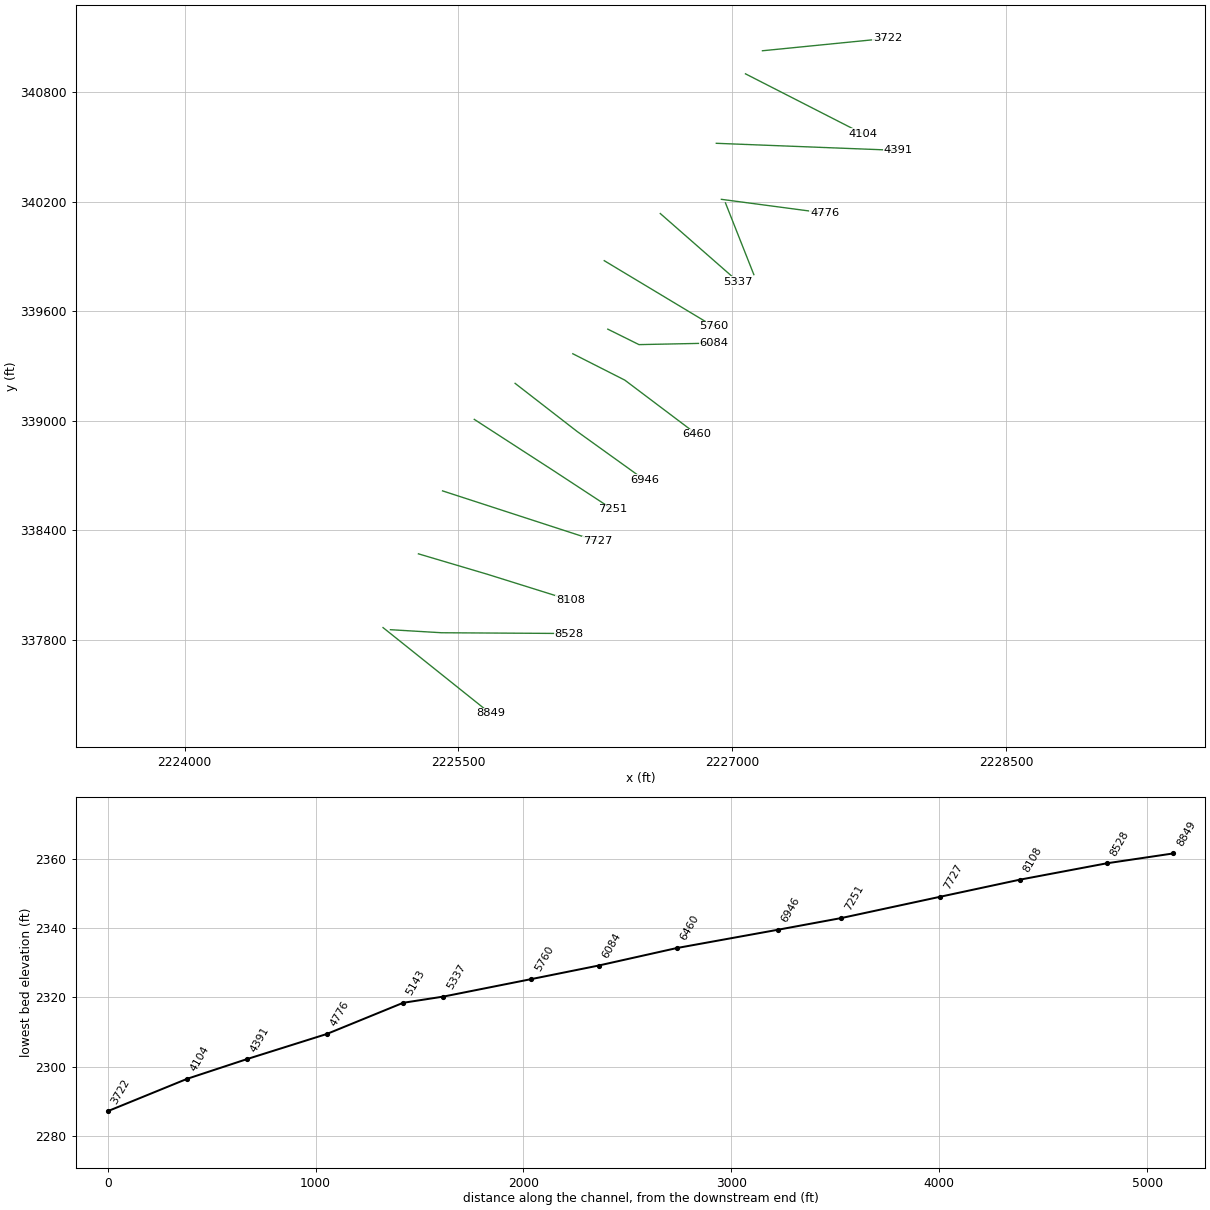
HEC-RAS study LAURELRN2.prj: LAURELRN2

--- LAURELRN2.g01 (geometry) --- (continued)

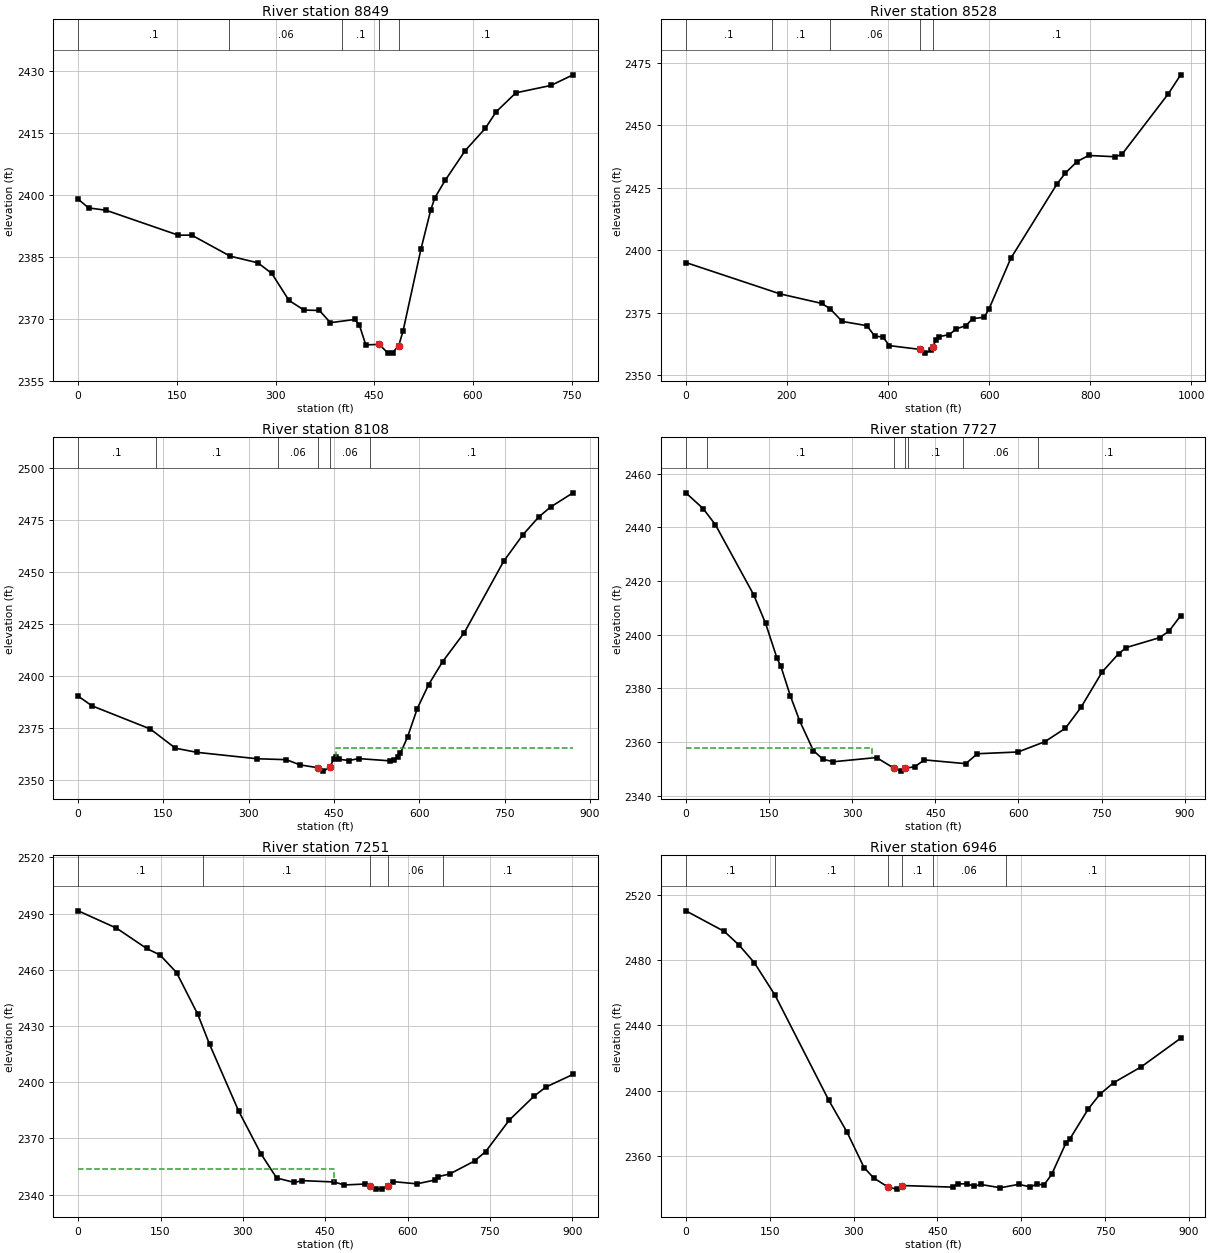
Type RM Length L Ch R = 1 ,8849    ,312.3,320.7,329.2
XS GIS Cut Line= 2
2225086.73838547337866.822688639 2225674.2385228337397.030977309
#Sta/Elev= 30
       0 2398.93    15.8 2396.81    42.2 2396.25   152.3  2390.2   172.6 2390.22
   231.1 2385.12   273.2 2383.51   294.4 2380.93   320.4 2374.41   343.3 2372.07
   366.7 2371.97   383.5 2369.01   420.3 2369.79   427.4 2368.47   437.2 2363.64
  457.882363.751   470.8 2361.64     478 2361.75  487.322363.483   493.8 2366.95
   521.2 2386.91   535.8 2396.21   542.3 2399.31   558.1 2403.53   588.4  2410.7
   618.8 2416.06   635.6 2420.12   665.4 2424.68   718.7 2426.47   752.2 2429.04
#Mann= 5 ,-1 , 0
       0      .1       0   229.6     .06       0  401.04      .1       0
  457.88    .045       0  487.32      .1       0
Bank Sta=457.88,487.32
XS Rating Curve= 0 ,0
Exp/Cntr=0.3,0.1

Type RM Length L Ch R = 1 ,8528    ,421.2,419.5,413.5
XS GIS Cut Line= 3
2225127.36330423337855.3643782292225407.57173331337838.697744891
2226105.48831648337834.531086564
#Sta/Elev= 30
       0 2395.02   186.4 2382.48   268.5 2378.68   284.9 2376.61   309.1 2371.47
   358.1 2369.76   373.5 2365.59   389.9 2365.22   402.4 2361.78  462.862360.282
     472 2358.78   485.1 2359.88   488.4 2361.31   494.9 2364.18   501.5  2365.4
   521.2 2366.19   534.3 2368.45     554 2369.79   567.1 2372.55   590.1 2373.16
   599.4 2376.38   642.6 2396.69   734.4 2426.58   750.8 2430.87   773.8 2435.44
   796.8 2437.86   849.3 2437.34   862.4 2438.28   954.2 2462.54   978.6 2470.12
#Mann= 5 ,-1 , 0
       0      .1       0  169.57      .1       0  284.71     .06       0
  462.86    .045       0   488.4      .1       0
Bank Sta=462.86,488.4
XS Rating Curve= 0 ,0
Exp/Cntr=0.3,0.1

Type RM Length L Ch R = 1 ,8108    ,381.1,381.6,380.8
XS GIS Cut Line= 3
2225280.48832606 338270.989203142225656.53022489338159.531092733
2226112.77996856338016.822716728
#Sta/Elev= 30
       0 2390.09    24.3 2385.44   126.7 2374.32   171.2 2365.04   208.8 2363.07
   314.7 2359.98   366.2 2359.54   390.2 2357.03  422.132355.651   431.4 2354.03
  442.522355.895   449.5 2359.79   454.1 2360.75   459.3 2359.73   476.1 2359.13
   493.5 2360.06   548.5 2358.97   555.2 2359.29   562.1 2360.89   566.7 2362.61
   579.3 2370.43   596.4 2384.09   616.4 2395.64   641.1 2406.73   679.3  2420.7
   748.3 2454.94   782.1 2467.67   810.2 2476.31   831.2 2481.11   870.3 2487.88
#Mann= 6 ,-1 , 0
       0      .1       0  136.16      .1       0  351.75     .06       0
  422.13    .045       0  442.52     .06       0  512.83      .1       0
#XS Ineff= 2 , 0
                          453.31         2365.33
Permanent Ineff=
       F       F
Bank Sta=422.13,442.52
XS Rating Curve= 0 ,0
Exp/Cntr=0.3,0.1

Type RM Length L Ch R = 1 ,7727    ,477,476,473.3
XS GIS Cut Line= 2
2225412.78005622338615.7808363882226261.73833205338339.739393726
#Sta/Elev= 30
       0  2452.8    31.2 2446.93    53.3 2440.93   122.3 2414.86   143.9 2404.14
   164.6 2391.09   171.5 2388.12   188.7 2377.04   205.6 2367.71   230.1 2356.76
     247 2353.59   265.5 2352.59     344 2354.17  375.912350.138   387.9 2349.11
  395.92 2350.22     413 2350.73   430.2  2353.3     505 2351.89   525.9 2355.59
   599.3 2356.24   647.6 2360.07   684.7 2365.07   712.8 2372.85   751.1 2386.07
     781 2392.92   794.5 2395.15   854.6 2398.83   871.8 2401.29   892.7 2407.05
#Mann= 7 ,-1 , 0
       0      .1       0   37.73      .1       0  375.91    .045       0
  395.92      .1       0  400.08      .1       0  500.59     .06       0
  634.95      .1       0
#XS Ineff= 2 , 0
          336.73 2357.64
Permanent Ineff=
       F       F
Bank Sta=375.91,395.92
XS Rating Curve= 0 ,0
Exp/Cntr=0.3,0.1

Type RM Length L Ch R = 1 ,7251    ,306,304.5,306.6
XS GIS Cut Line= 3
2225586.53003681339007.4824808092226015.69682939338729.704493061
 2226342.0856123338515.815813228
#Sta/Elev= 30
       0 2491.46    69.8 2482.23   124.8 2471.36     149 2467.92   179.2 2458.54
   217.9 2436.22   239.5 2420.15   292.1 2384.77   333.1 2361.73   361.6 2348.87
   393.7 2346.52   408.6 2347.49     466 2346.77     485 2345.17   522.7 2345.67
  531.972344.476   542.3 2342.95   554.1 2343.07  563.692344.884   573.7 2346.97
   616.9 2345.77   650.9 2347.87   655.6 2349.59     677 2351.05     722 2357.96
   742.4 2363.02   785.5 2379.85     831 2392.69   852.3 2397.46   901.4 2404.16
#Mann= 5 ,-1 , 0
       0      .1       0  226.96      .1       0  531.97    .045       0
  563.69     .06       0  665.38      .1       0
#XS Ineff= 2 , 0
          465.76 2353.47
Permanent Ineff=
       F       F
Bank Sta=531.97,563.69
XS Rating Curve= 0 ,0
Exp/Cntr=0.3,0.1

Type RM Length L Ch R = 1 ,6946    ,486.7,486.5,489.4
XS GIS Cut Line= 3
2225810.14113814339204.7045273042226150.41900089338940.815619394
2226519.86347197338675.537934721
#Sta/Elev= 30
       0 2510.28    68.9 2497.62    95.2 2489.26   122.5 2478.48   159.5 2458.59
   255.8 2394.05   288.5 2374.49   318.9  2352.8   336.1 2346.42  362.112340.756
   377.4 2339.57  387.622341.769   477.6  2340.8   486.6 2342.74   502.8 2342.87
   515.8 2341.34   527.5 2342.43   562.8 2340.41   595.7  2342.5   615.9 2340.97
   628.6 2342.65   640.7  2342.1   654.5 2348.56   680.1 2367.88   687.4 2370.51
   720.3 2388.87   741.1 2397.86   765.3 2404.82   815.1 2414.65   885.4 2432.11
#Mann= 6 ,-1 , 0
       0      .1       0  159.67      .1       0  362.11    .045       0
  387.62      .1       0  442.09     .06       0  572.21      .1       0
Bank Sta=362.11,387.62
XS Rating Curve= 0 ,0
Exp/Cntr=0.3,0.1

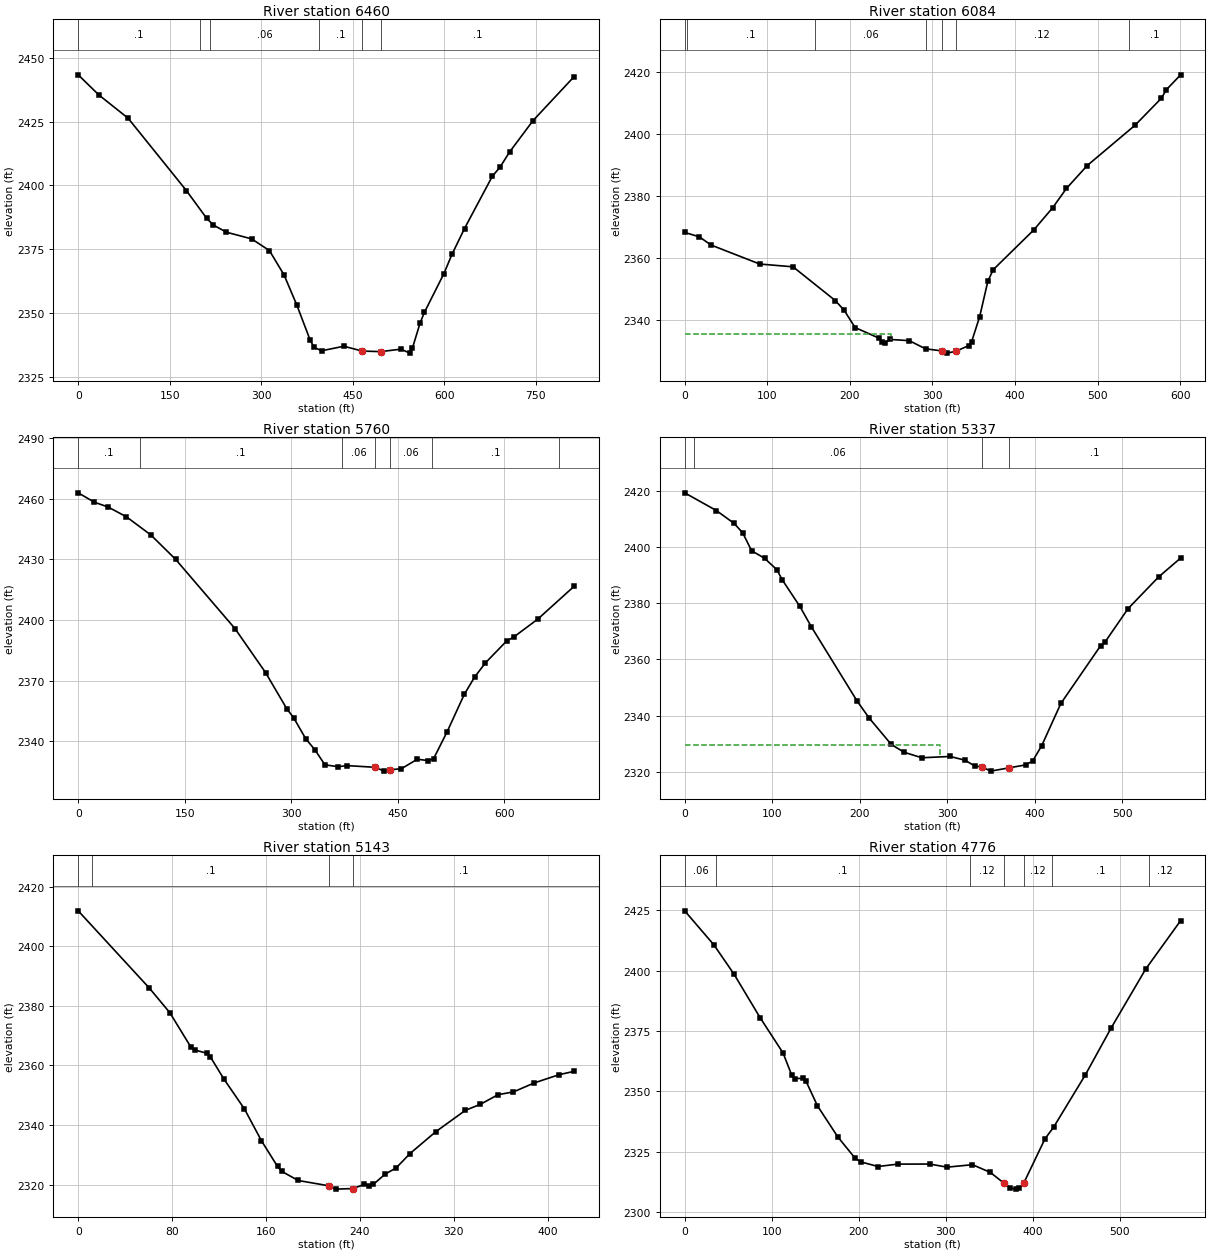
Type RM Length L Ch R = 1 ,6460    ,368.1,376.2,384.1
XS GIS Cut Line= 3
2226126.24057156 339367.027693482226410.96277113339222.583428562
2226805.40719222338925.361253977
#Sta/Elev= 30
       0 2443.31      34 2435.39    81.7 2426.34   177.5 2397.93   210.6  2387.1
   221.6 2384.47   242.9 2381.66   284.4 2379.03   313.6 2374.44   337.6 2364.87
   358.4 2353.14   380.5 2339.27   386.9 2336.51   399.2 2335.21   435.7 2336.98
  465.652335.086  495.892334.868   529.4 2335.84   543.5 2334.28   548.1  2336.3
   560.4 2345.95   567.6 2350.22   599.7 2365.46   612.8 2372.94   633.4  2383.1
   679.3 2403.68   691.3 2407.01   707.4  2413.1   745.8 2425.38   813.2 2442.62
#Mann= 6 ,-1 , 0
       0      .1       0  199.63      .1       0   216.1     .06       0
  395.25      .1       0  465.65    .045       0  495.89      .1       0
Bank Sta=465.65,495.89
XS Rating Curve= 0 ,0
Exp/Cntr=0.3,0.1

Type RM Length L Ch R = 1 ,6084    ,327.9,323.8,317.4
XS GIS Cut Line= 3
2226317.90718298339501.7501930592226488.74050272339417.027921557
2226898.46278039339425.361238226
#Sta/Elev= 30
       0 2368.18    17.7 2366.77    31.9 2364.12    90.9 2357.98   131.2 2357.08
   182.5 2346.16   193.2 2343.02   206.3 2337.49   235.1 2334.07   239.1 2332.72
   242.4 2332.47   248.9 2333.63   271.9 2333.25   291.6 2330.62   312.1 2329.91
   317.9 2329.22  328.642329.857   344.1 2331.67   347.4 2332.87   357.2 2341.01
   367.1 2352.44   373.6 2356.16   422.7 2368.99   445.6 2376.16   462.2 2382.37
   487.4 2389.77   545.3 2402.78   577.1 2411.47   583.4  2414.3   600.5 2419.06
#Mann= 7 ,-1 , 0
       0      .1       0    2.64      .1       0  158.27     .06       0
  292.27     .12       0   312.1    .045       0  328.64     .12       0
  537.55      .1       0
#XS Ineff= 2 , 0
          249.97 2335.45
Permanent Ineff=
       F       F
Bank Sta=312.1,328.64
XS Rating Curve= 0 ,0
Exp/Cntr=0.3,0.1

Type RM Length L Ch R = 1 ,5760    ,421.5,422.4,417.5
XS GIS Cut Line= 2
2226298.46266806339876.7500992272226897.07367556339517.027721554
#Sta/Elev= 30
       0 2462.84    22.4 2458.25    42.2  2455.8    67.7 2451.04   102.4 2441.99
   137.2 2429.95   220.9 2395.68   263.9 2373.97   293.8 2356.07   303.4 2351.68
   320.6 2341.18   333.2 2335.92   347.4 2328.42   366.5 2327.47     378 2328.04
  418.022327.197   430.7  2325.3  438.652325.942   455.2 2326.51   477.5 2331.18
   492.8 2330.51   500.5 2331.48   519.6 2344.81   543.6 2363.18   558.1 2371.72
   573.2  2378.7   603.4 2389.65     613 2391.48   647.3 2400.46   698.4 2416.66
#Mann= 7 ,-1 , 0
       0      .1       0      87      .1       0  371.68     .06       0
  418.02    .045       0  438.65     .06       0  498.64      .1       0
  676.66     .12       0
Bank Sta=418.02,438.65
XS Rating Curve= 0 ,0
Exp/Cntr=0.3,0.1

Type RM Length L Ch R = 1 ,5337    ,199.2,193.9,185.8
XS GIS Cut Line= 2
2226605.40726414340135.0832439812227031.79584706339761.472114563
#Sta/Elev= 30
       0 2419.33    36.2 2413.03    56.6 2408.42    66.3  2405.1    76.5 2398.73
    91.4    2396   105.5 2391.92   111.3 2388.47   131.7 2378.88   144.8 2371.63
   197.1  2345.2   210.9 2339.14   236.1 2329.77   250.7 2326.98     271 2325.01
   303.5 2325.47   320.4 2324.14   331.4  2322.1  340.012321.738   349.8 2320.25
   370.32321.391   389.6 2322.46   397.8 2323.87   408.2 2329.37     430 2344.33
   475.6 2364.97   480.7 2366.31   506.8 2378.09   541.7 2389.37   566.9 2396.11
#Mann= 4 ,-1 , 0
       0     .12       0   10.88     .06       0  340.01    .045       0
   370.3      .1       0
#XS Ineff= 2 , 0
          292.02 2329.42
Permanent Ineff=
       F       F
Bank Sta=340.01,370.3
XS Rating Curve= 0 ,0
Exp/Cntr=0.3,0.1

Type RM Length L Ch R = 1 ,5143    ,351.7,367.4,375.8
XS GIS Cut Line= 2
2226962.35143214340193.4167887272227117.90722339339800.361144394
#Sta/Elev= 30
       0  2411.9    60.5 2386.01    78.1 2377.69    95.8  2366.3    99.3 2365.18
   109.9 2364.05   112.6 2362.88     124 2355.52   141.7 2345.36   156.2 2334.68
   169.9 2326.05   173.4 2324.42   187.5 2321.35  213.75 2319.56   219.3 2318.45
  234.082318.639     244 2320.06   247.5 2319.63   251.6 2320.07   261.7 2323.51
     271 2325.58   282.8  2330.4   304.7 2337.71     330 2344.91   342.8 2346.93
   357.8 2350.16     371  2351.1   388.6  2354.1   409.8 2356.87   422.7 2358.01
#Mann= 4 ,-1 , 0
       0     .06       0   11.58      .1       0  213.75    .045       0
  234.08      .1       0
Bank Sta=213.75,234.08
XS Rating Curve= 0 ,0
Exp/Cntr=0.3,0.1

Type RM Length L Ch R = 1 ,4776    ,380.9,385.5,384.4
XS GIS Cut Line= 2
2226940.12936372340212.8613036422227505.40710455340137.861125559
#Sta/Elev= 30
       0 2424.81    33.7 2410.64    56.8 2398.52    86.6 2380.58   113.1 2365.89
     123 2356.76   126.3 2355.28   136.3 2355.35   139.6 2354.11   152.6 2344.01
     176  2331.1   195.8 2322.32   202.4 2320.73   222.3 2318.81   245.5 2319.81
   281.9 2319.82   301.7 2318.54   330.9 2319.56   351.4 2316.37  367.052311.906
   374.5 2309.88   380.6 2309.43   384.5 2309.71  389.762311.857   414.3 2330.32
   424.2 2335.12   460.6 2356.76   490.4 2376.29   530.1  2400.7   570.2 2420.72
#Mann= 7 ,-1 , 0
       0     .06       0   36.43      .1       0   327.8     .12       0
  367.05    .045       0  389.76     .12       0  422.04      .1       0
  534.29     .12       0
Bank Sta=367.05,389.76
XS Rating Curve= 0 ,0
Exp/Cntr=0.3,0.1

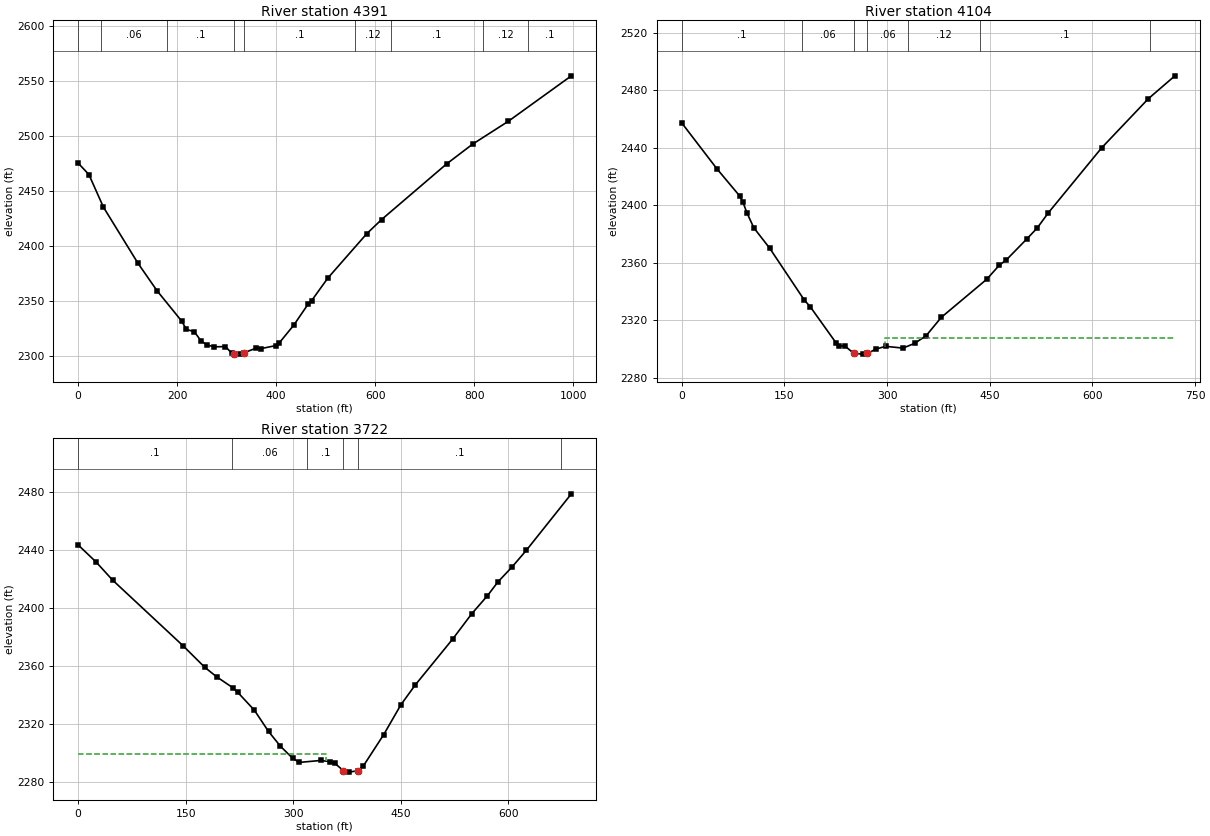
Type RM Length L Ch R = 1 ,4391    ,290.1,286.2,281.4
XS GIS Cut Line= 2
2226912.35153213340519.8055716462227907.71502697340480.982158482
#Sta/Elev= 30
       0 2475.58    21.8 2465.16    51.3 2435.42   120.9 2384.64   159.7 2359.52
   208.9 2332.28   218.8 2324.59   234.7 2322.45   248.3 2314.15     260 2310.56
   274.6 2308.76   297.6 2308.99   310.7 2302.83  314.962302.432   327.1 2302.14
  335.022303.398     360 2307.63   369.8 2307.18   399.4 2309.91   406.6 2312.53
   435.5 2328.42     465 2347.82   471.6 2350.69   504.4  2371.2   583.2 2411.57
   612.8 2424.24   744.1 2474.74   796.7 2492.71   868.9  2513.5   996.1 2554.72
#Mann= 9 ,-1 , 0
       0     .12       0   46.82     .06       0  179.43      .1       0
  314.96    .045       0  335.02      .1       0  558.44     .12       0
  632.43      .1       0  816.93     .12       0  909.49      .1       0
Bank Sta=314.96,335.02
XS Rating Curve= 0 ,0
Exp/Cntr=0.3,0.1

Type RM Length L Ch R = 1 ,4104    ,376.1,382.3,387.6
XS GIS Cut Line= 2
2227072.07365364340900.3612409832227713.74034931340572.583353221
#Sta/Elev= 30
       0 2457.34    51.4 2425.42    84.6 2406.55    89.2 2402.52    95.6 2394.46
   105.5 2384.29   128.8    2370   179.4 2333.91   187.7 2329.53   225.7  2304.2
   230.6  2302.4   239.3 2301.84  251.282297.034   264.8 2296.47  271.442296.986
   284.3 2300.07   298.2  2301.9   323.3 2300.66   340.4 2303.97   357.2  2309.3
   379.3 2322.04   445.6 2348.49     464 2358.27   474.5 2362.09   504.5  2376.7
   519.3 2384.11   535.4 2394.58   613.5 2439.89   681.7 2474.05   720.5 2489.97
#Mann= 7 ,-1 , 0
       0      .1       0  175.17     .06       0  251.28    .045       0
  271.44     .06       0   331.2     .12       0  435.54      .1       0
  684.34     .12       0
#XS Ineff= 2 , 0
                             297         2307.47
Permanent Ineff=
       F       F
Bank Sta=251.28,271.44
XS Rating Curve= 0 ,0
Exp/Cntr=0.3,0.1

Type RM Length L Ch R = 1 ,3722    ,261.1,264.4,263.9
XS GIS Cut Line= 2
2227165.12924181341026.7500958142227849.85162564341094.805733979
#Sta/Elev= 30
       0 2443.78      25 2432.04    48.1 2419.52     147 2373.96   176.7 2359.38
   193.2 2352.86   216.2 2345.17   222.8 2342.06   245.9 2329.81   265.7 2315.13
   282.2 2305.01   299.2 2296.68   308.6 2293.81   338.2 2295.13   351.4 2294.38
     358 2293.22   369.92288.217   377.8  2287.1  390.282288.076   397.6  2291.1
   426.4 2313.01   450.3 2333.53   470.1 2347.05   522.9 2379.07   549.2 2396.33
   571.1 2408.75   585.5 2418.16   605.3 2428.52   625.1 2439.91   688.1 2478.98
#Mann= 6 ,-1 , 0
       0      .1       0  215.19     .06       0  319.92      .1       0
   369.9    .045       0  390.28      .1       0  673.82     .12       0
#XS Ineff= 2 , 0
          345.44 2299.94
Permanent Ineff=
       F       F
Bank Sta=369.9,390.28
XS Rating Curve= 0 ,0
Exp/Cntr=0.3,0.1