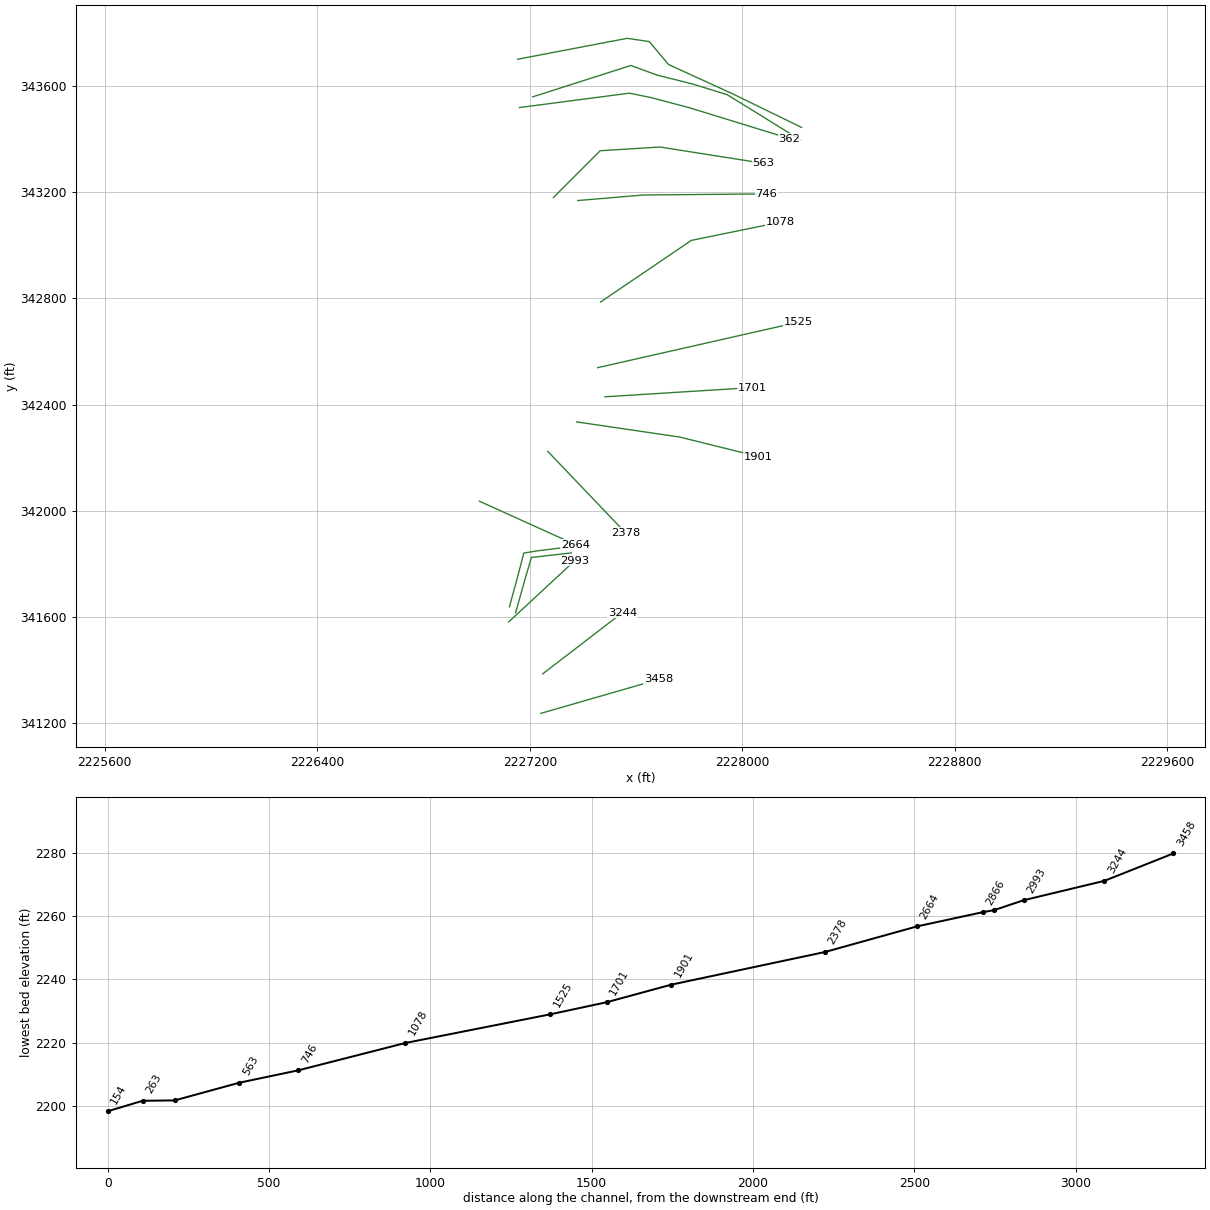
HEC-RAS study LAURELRN2.prj: LAURELRN2

--- LAURELRN2.g01 (geometry) --- (continued)

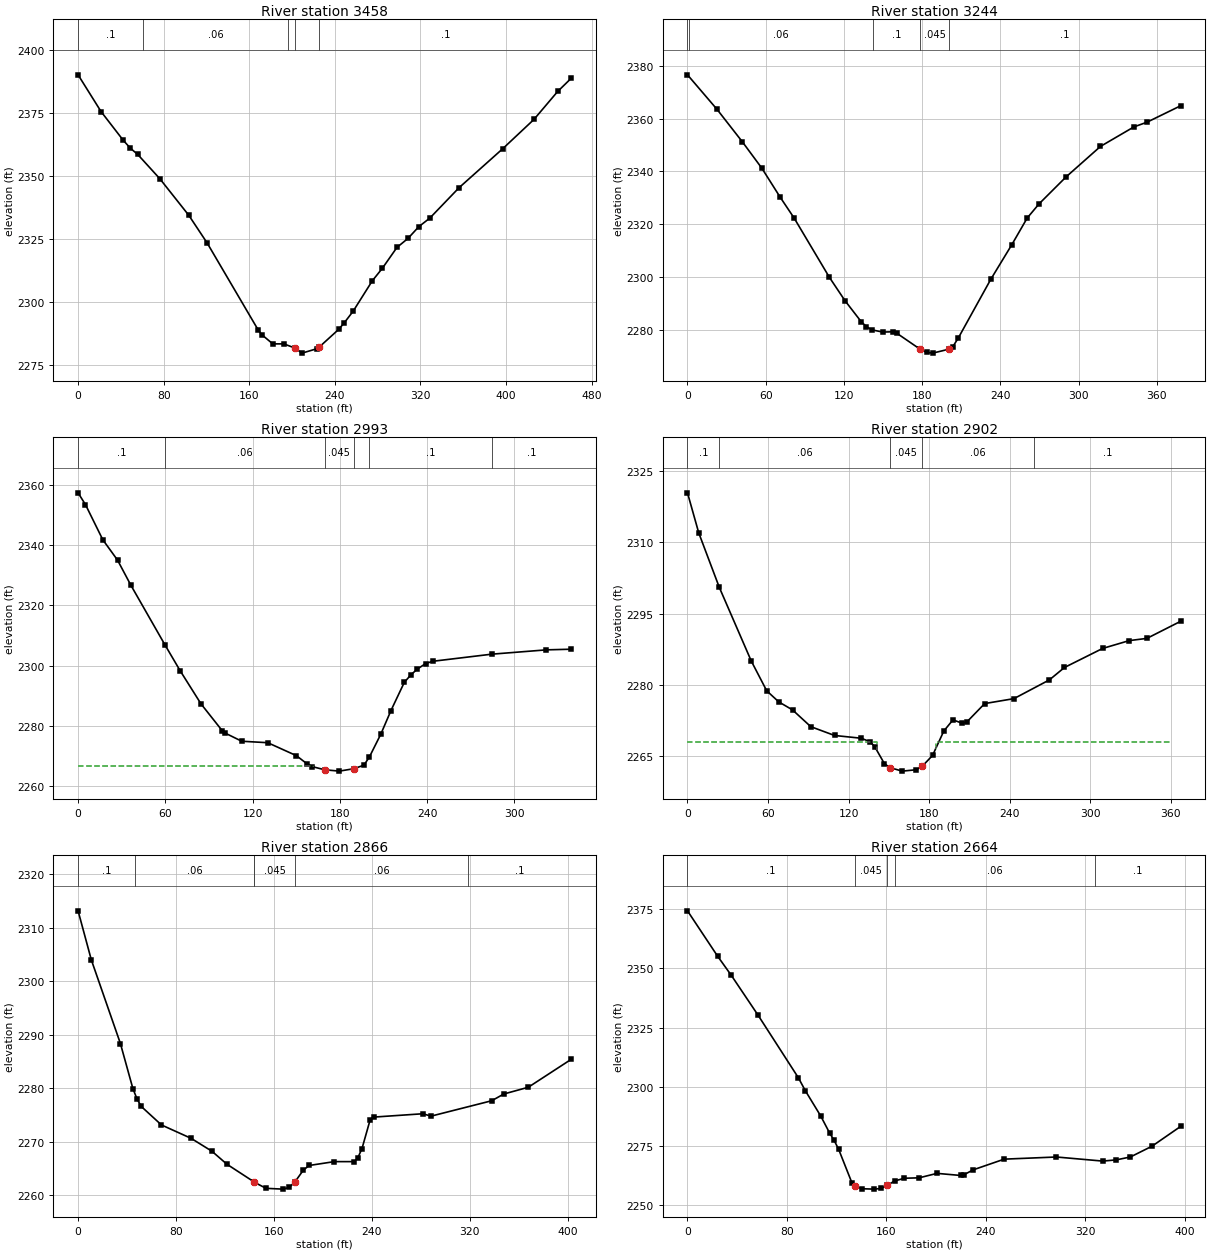
Type RM Length L Ch R = 1 ,3458    ,207.8,213.8,218.3
XS GIS Cut Line= 2
2227241.51819664341237.8612221482227684.57374097341365.638853729
#Sta/Elev= 30
       0 2390.14    21.5 2375.55      42 2364.29    48.8 2361.06    55.7 2358.58
    76.4 2348.93   103.5 2334.41   120.6 2323.47   168.4  2288.9   171.7 2287.07
     182 2283.41   192.3 2283.41  202.762281.753   209.3 2279.74     223 2281.46
  225.652282.231   243.5 2289.12   248.6 2291.65   257.1 2296.35   275.1 2308.47
   284.4 2313.38   298.1 2321.68   308.4 2325.25   318.6 2329.94   328.8  2333.3
   356.2 2345.39     397 2360.84   426.2 2372.47   448.3 2383.53   461.1 2388.83
#Mann= 5 ,-1 , 0
       0      .1       0   60.99     .06       0  196.67      .1       0
  202.76    .045       0  225.65      .1       0
Bank Sta=202.76,225.65
XS Rating Curve= 0 ,0
Exp/Cntr=0.3,0.1

Type RM Length L Ch R = 1 ,3244    ,249.5,250.3,251.2
XS GIS Cut Line= 2
2227248.46273655341386.4721453932227548.46279272341617.027786642
#Sta/Elev= 30
       0 2376.57    22.7 2363.46    42.2 2351.11    57.1 2341.14    71.1 2330.19
    81.9 2322.21   108.8 2299.86   120.8 2290.98   133.2 2283.04   137.3 2281.11
   141.3 2279.92   149.7 2279.07     158 2279.17   160.5 2278.65   178.7 2272.48
   178.7 2272.47   183.4 2271.38   188.1 2271.08   200.3 2272.54   203.5  2273.5
   207.7 2276.77   232.6    2299   248.8 2312.18   260.6 2322.29   269.7 2327.66
   290.4 2337.86   316.8 2349.43   342.5 2356.84   352.5 2358.61   378.4 2364.86
#Mann= 5 ,-1 , 0
       0      .1       0    1.19     .06       0  142.27      .1       0
   178.7    .045       0   200.3      .1       0
Bank Sta=178.7,200.3
XS Rating Curve= 0 ,0
Exp/Cntr=0.3,0.1

Type RM Length L Ch R = 1 ,2993    ,86.5,91.8,98.6
XS GIS Cut Line= 2
2227120.68477689341582.305743232 2227369.2961563341812.861056387
#Sta/Elev= 30
       0 2357.31     5.1 2353.38      17 2341.74    27.1    2335    36.3 2326.64
    59.6 2306.96    70.1 2298.33    84.5 2287.28      99 2278.43   101.3 2277.54
   112.5 2274.88   130.4 2274.39   150.1 2270.09   157.2 2267.45   161.1 2266.44
  169.562265.406   179.6 2264.96  189.582265.767   196.5 2266.93   200.3 2269.69
   208.1 2277.21   215.1 2285.07   224.3 2294.45     229 2297.02   233.3 2298.84
   238.9 2300.66   243.8 2301.41   284.4 2303.77   321.9  2305.2   339.1 2305.42
#Mann= 6 ,-1 , 0
       0      .1       0    59.6     .06       0  169.56    .045       0
  189.58     .06       0   200.3      .1       0   284.4      .1       0
#XS Ineff= 2 , 0
           161.5  2266.7   197.6          2266.7
Permanent Ineff=
       F       F
Bank Sta=169.56,189.58
XS Rating Curve= 0 ,0
Exp/Cntr=0.5,0.3

Type RM Length L Ch R = 1 ,2902    ,31.1,35.4,35.5
XS GIS Cut Line= 6
2227146.68997422341616.9785741422227184.56741877341751.878999248
2227197.14125731341794.3528167412227206.30410014 341825.17142146
2227217.90101352 341826.014662972227356.13443722341841.978780314
#Sta/Elev= 30
       0 2320.45     8.4    2312    23.7 2300.53    47.5 2285.02      59 2278.75
      68 2276.41    78.2 2274.73    91.8  2271.2   109.5 2269.34   129.3 2268.76
     136 2268.02   139.5 2266.95   146.7 2263.37  150.942262.551   159.9 2261.83
   170.5 2262.12  174.772262.847   182.5 2265.14   190.9 2270.29   197.7 2272.63
   204.6 2271.91     208 2272.18   221.3 2276.06   243.1  2277.1   269.5 2281.05
   280.7 2283.66   309.1 2287.67   328.9 2289.32   342.1 2289.79   367.3  2293.4
#Mann= 5 ,-1 , 0
       0      .1       0    23.6     .06       0  150.94    .045       0
  174.77     .06       0   258.1      .1       0
#XS Ineff= 2 ,-1
       0  140.94    2268  184.77   360.3    2268
Permanent Ineff=
       F       F
Bank Sta=150.94,174.77
XS Rating Curve= 0 ,0
Exp/Cntr=0.5,0.3

Type RM Length L Ch R = 1 ,2866    ,231.5,202.5,181.5
XS GIS Cut Line= 6
2227123.41806872341639.1775132142227159.02120981341770.302742768
2227177.54934341 341841.494753672227193.76016462341843.939913535
2227223.45644861341849.0534797422227369.46774389341866.978730306
#Sta/Elev= 30
       0  2313.2    10.8 2304.05    34.6 2288.39    44.8 2279.96    48.2 2278.02
    51.6 2276.64    68.1 2273.18    92.4 2270.67   109.4 2268.26   121.6 2265.84
   143.4 2262.59     144 2262.47   153.6 2261.33   167.3 2261.18   172.6 2261.49
   177.3 2262.56   184.1 2264.73   188.8  2265.6   209.4 2266.32   225.8 2266.32
   228.7 2267.08     232 2268.75   238.7 2274.16     242 2274.65   281.8 2275.27
   288.4 2274.82     338  2277.7   347.9 2278.96   367.9 2280.22   403.1 2285.46
#Mann= 6 ,-1 , 0
       0      .1       0    46.9     .06       0   143.4    .045       0
     144    .045       0   177.3     .06       0   318.7      .1       0
Bank Sta=144,177.3
XS Rating Curve= 0 ,0
Exp/Cntr=0.5,0.3

Type RM Length L Ch R = 1 ,2664    ,292.7,285.8,280.2
XS GIS Cut Line= 2
2227010.43991864 342036.49249889 2227371.8985133341872.950831234
#Sta/Elev= 30
       0 2374.35    24.3 2355.12    35.1 2347.19    56.7 2330.29    89.1 2303.86
    94.8  2298.3   107.1 2287.68   114.3 2280.45   117.9 2277.36   121.5 2273.64
   132.3 2259.31  134.432258.215   140.5 2256.88   150.3 2256.72   155.3 2256.99
  160.662258.334   166.5 2260.15   174.4 2261.32   186.3  2261.5   200.7 2263.38
   219.8 2262.49   222.3 2262.78   229.7 2264.86   254.7 2269.39   296.7  2270.3
     334 2268.57   344.8 2269.08   356.2 2270.31   373.6 2274.87   396.7 2283.26
#Mann= 5 ,-1 , 0
       0      .1       0  134.43    .045       0  160.66      .1       0
   166.5     .06       0  327.64      .1       0
Bank Sta=134.43,160.66
XS Rating Curve= 0 ,0
Exp/Cntr=0.3,0.1

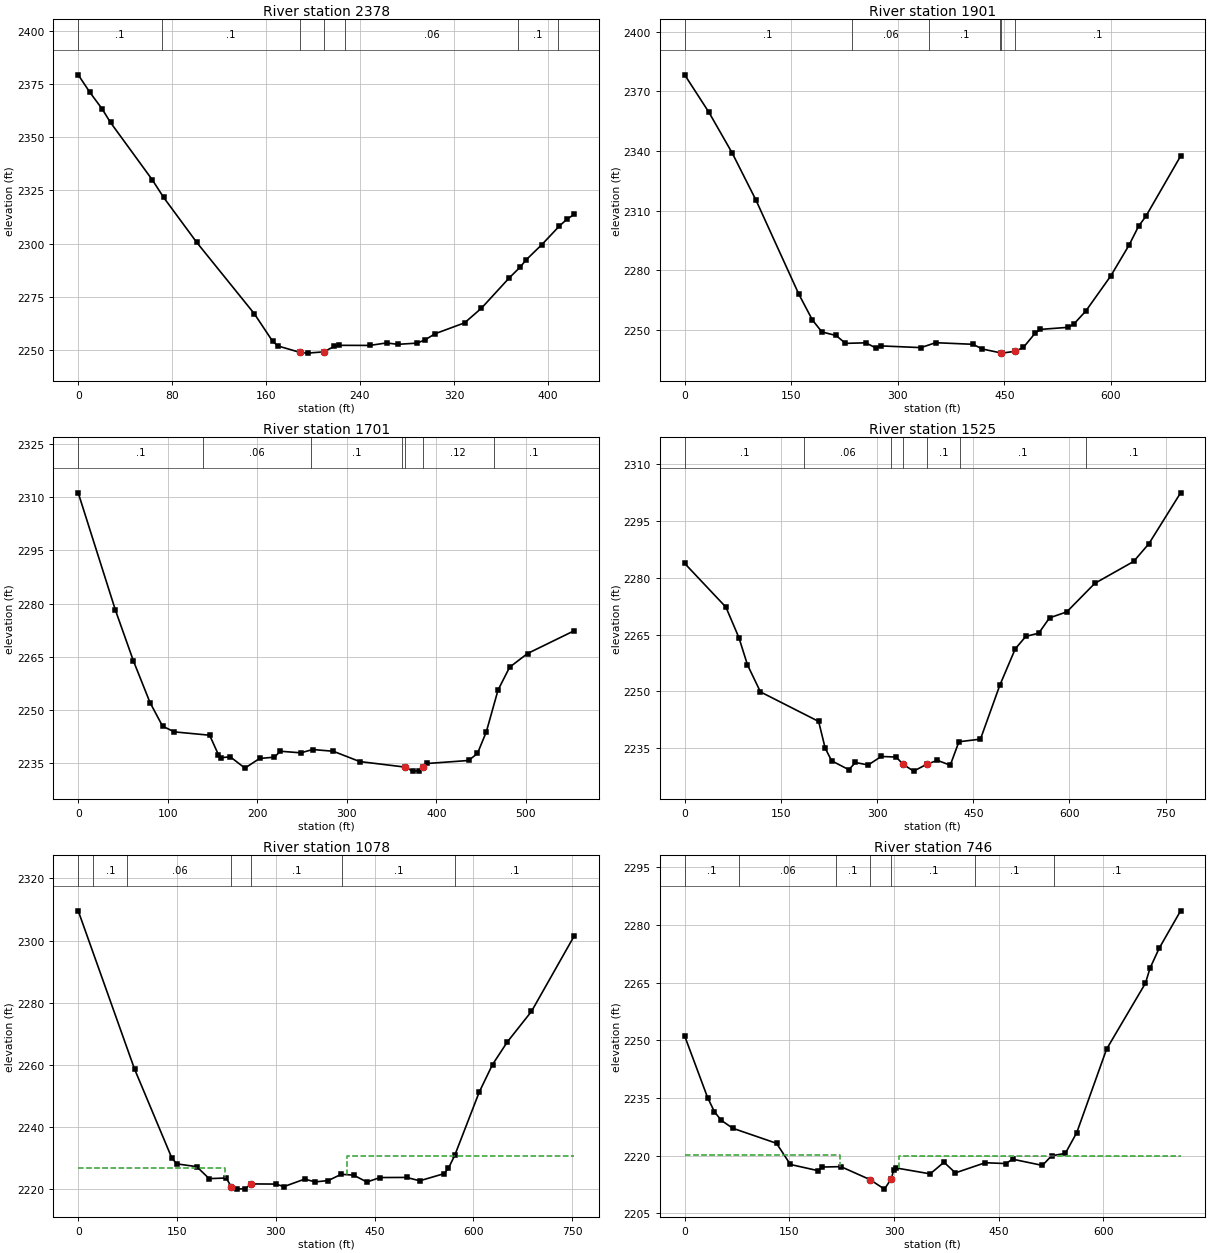
Type RM Length L Ch R = 1 ,2378    ,470.8,477.3,482
XS GIS Cut Line= 2
2227267.90725148342223.9721108082227559.57366289341918.416619554
#Sta/Elev= 30
       0 2379.23      10 2370.95    20.2 2363.37    27.5 2356.87      63 2330.02
    72.8 2321.66     101 2300.55     150  2267.1   165.5 2254.24   170.1 2251.99
  188.992248.944   195.3 2248.62  208.992249.211     218 2251.74   222.5 2252.28
   248.3 2252.23   262.6  2253.4   272.2 2252.75   288.5 2253.31   295.1 2254.77
   304.2 2257.77   329.1 2262.84   343.4 2269.69   367.1 2283.92   376.7 2289.15
   381.3 2292.29   394.9 2299.55   409.9 2308.31   416.1 2311.39   422.4 2313.71
#Mann= 7 ,-1 , 0
       0      .1       0    71.6      .1       0  188.99    .045       0
  208.99      .1       0  227.39     .06       0  374.28      .1       0
   408.4      .1       0
Bank Sta=188.99,208.99
XS Rating Curve= 0 ,0
Exp/Cntr=0.3,0.1

Type RM Length L Ch R = 1 ,1901    ,196.2,199.7,202.3
XS GIS Cut Line= 3
2227376.24036814342335.0834371452227763.74057738342278.138997227
2228060.96275197342204.527923971
#Sta/Elev= 30
       0 2378.31      34 2359.52    67.1 2338.82   100.3 2315.28   160.6 2267.96
   179.7 2254.98   193.1 2248.94     213 2247.16   226.3 2243.19   254.9 2243.47
   269.4 2240.82     276 2241.92   332.4 2241.05   353.2 2243.53   405.6 2242.72
   419.1 2240.33  444.712238.409   446.2 2238.28  464.732239.189   476.6 2241.13
   493.5 2248.45   500.3 2250.21   539.9 2251.27     548 2253.05   564.5 2259.47
   599.5 2277.06   625.3 2292.58   638.8 2302.18     649 2307.11   697.9 2337.44
#Mann= 6 ,-1 , 0
       0      .1       0  235.06     .06       0  344.14      .1       0
  443.64      .1       0  444.71    .045       0  464.73      .1       0
Bank Sta=444.71,464.73
XS Rating Curve= 0 ,0
Exp/Cntr=0.3,0.1

Type RM Length L Ch R = 1 ,1701    ,174.9,176,176.4
XS GIS Cut Line= 2
2227483.18503614342429.5278020652228035.96280198342464.250173554
#Sta/Elev= 30
       0 2311.25    41.6 2278.12    61.6 2263.88    80.2 2252.09    94.2 2245.44
   107.3 2243.82   146.8 2242.88   156.6 2237.38   159.9 2236.55   169.8 2236.79
   186.2  2233.6   202.6 2236.33   219.1 2236.68   225.7 2238.36   248.7 2237.91
   261.8 2238.84   284.8 2238.36   314.4 2235.45  365.082233.887   373.6 2232.75
   380.2 2232.84  385.122233.974     390 2234.91     436 2235.75   445.9 2237.73
   455.8 2243.84   468.9 2255.63   481.8 2262.05   501.8 2265.92   553.9 2272.34
#Mann= 7 ,-1 , 0
       0      .1       0  139.74     .06       0  260.13      .1       0
  361.99     .12       0  365.08    .045       0  385.12     .12       0
  463.85      .1       0
Bank Sta=365.08,385.12
XS Rating Curve= 0 ,0
Exp/Cntr=0.3,0.1

Type RM Length L Ch R = 1 ,1525    ,440.9,447.4,450.5
XS GIS Cut Line= 2
2227455.40720455342539.2500235592228209.57367522342710.083343312
#Sta/Elev= 30
       0  2283.8    64.3 2272.24    84.5 2264.21    97.9    2257   118.1 2249.85
   208.9 2242.04     219 2235.01   229.1 2231.65     256 2229.28   266.1 2231.19
   286.3 2230.54   306.5 2232.79     330 2232.62     340 2230.77     357 2228.91
  377.452230.718     394 2231.76   414.1 2230.47   427.6 2236.67   461.2 2237.36
   491.5 2251.66   515.5 2261.23   531.9 2264.51   552.1 2265.37   568.9 2269.41
   595.8 2270.99   639.5 2278.53   700.1 2284.32   723.9 2289.02   773.3 2302.45
#Mann= 7 ,-1 , 0
       0      .1       0  186.16     .06       0  322.05      .1       0
     340    .045       0  377.45      .1       0  429.16      .1       0
  626.54      .1       0
Bank Sta=340,377.45
XS Rating Curve= 0 ,0
Exp/Cntr=0.3,0.1

Type RM Length L Ch R = 1 ,1078    ,335.5,331.5,318.5
XS GIS Cut Line= 3
2227466.51807472342786.4722981452227808.18504231343018.416716143
2228141.51836513343086.472354308
#Sta/Elev= 30
       0 2309.57    85.5 2258.61   142.2  2229.9   149.6 2228.04     180 2227.12
   198.9 2223.27   224.8 2223.48  232.432220.645   240.8 2219.89     254 2220.06
   262.2 2221.57   300.3 2221.52   312.3 2220.69   343.9 2223.12   359.8 2222.22
   379.6 2222.64   399.4 2224.67   418.3  2224.4   438.4 2222.18   458.4 2223.62
   498.6 2223.66   518.7 2222.58   555.6 2224.87   562.3 2226.62     572 2230.85
   609.1 2251.19   629.2 2260.03   651.9 2267.38   688.4 2277.16   753.2 2301.44
#Mann= 7 ,-1 , 0
       0      .1       0   22.48      .1       0   74.84     .06       0
  232.43    .045       0   262.2      .1       0   400.4      .1       0
  572.73      .1       0
#XS Ineff= 2 , 0
          222.75 2226.68  407.47         2230.45
Permanent Ineff=
       F       F
Bank Sta=232.43,262.2
XS Rating Curve= 0 ,0
Exp/Cntr=0.3,0.1

Type RM Length L Ch R = 1 ,746     ,180.6,183.5,181.8
XS GIS Cut Line= 3
2227380.40702647343168.4167442322227629.01807781343189.250035897
 2228090.1293603343193.416694224
#Sta/Elev= 30
       0 2251.11    32.8 2235.11    42.7 2231.37    52.6 2229.14      69  2227.1
   131.6 2223.19   151.4 2217.69   190.9 2216.08   197.4 2217.02   223.8 2217.12
   265.5 2213.75   286.2 2211.27   296.1 2213.97   299.3 2216.14   302.6 2216.79
   351.8 2215.24   371.5 2218.26   387.9  2215.5   430.6 2218.14   460.1 2217.92
   469.9 2219.06   512.6 2217.44   525.7 2219.94   545.4 2220.57   561.8 2225.98
   604.5 2247.69   660.2 2264.85   666.8 2268.77   679.9 2273.95   710.6 2283.68
#Mann= 7 ,-1 , 0
       0      .1       0   78.45     .06       0  217.38      .1       0
   265.5    .045       0   296.1      .1       0  416.35      .1       0
  528.67      .1       0
#XS Ineff= 2 , 0
           222.3 2220.05  306.51         2219.95
Permanent Ineff=
       F       F
Bank Sta=265.5,296.1
XS Rating Curve= 0 ,0
Exp/Cntr=0.3,0.1

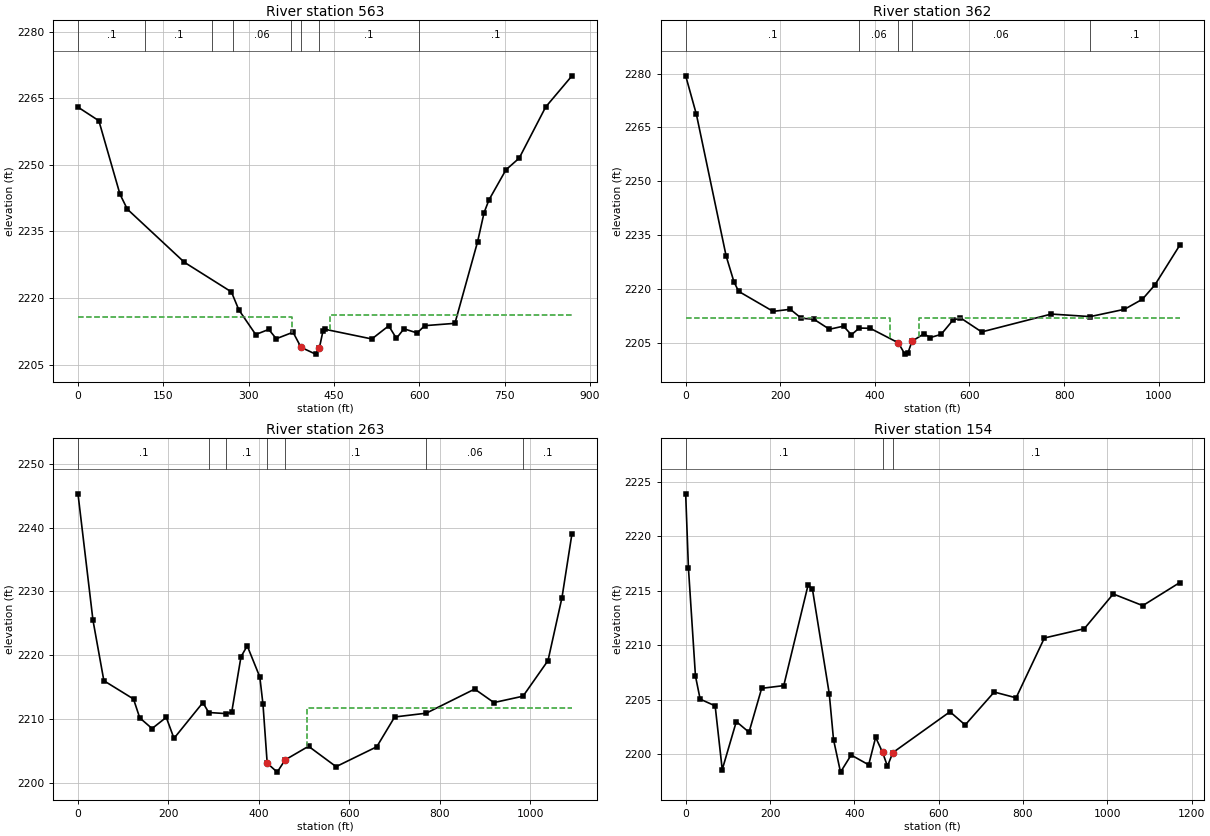
Type RM Length L Ch R = 1 ,563     ,203.8,200.2,196
XS GIS Cut Line= 4
2227288.74054314343179.5279424792227465.12929797343355.916697308
2227690.12917605343369.8054490542228079.01816206343308.694350809
#Sta/Elev= 30
       0 2263.03    36.7 2259.96    73.8  2243.4    86.7 2240.03     187 2228.05
   269.7 2221.37   282.8 2217.32   312.4 2211.76   335.4 2212.91   348.6 2210.81
   378.1 2212.28  392.032208.883   417.6 2207.34   424.2 2208.63   430.7 2212.54
     434 2212.95   516.6 2210.76   546.3 2213.72   559.8  2210.9   573.1 2213.05
   596.3 2212.11   609.6 2213.76   662.7 2214.28   702.6  2232.7   713.9 2239.21
   722.5  2242.1   752.4  2248.9   775.7 2251.53   822.2 2263.05   868.5 2270.09
#Mann= 8 ,-1 , 0
       0      .1       0   118.1      .1       0   235.4      .1       0
  272.54     .06       0  374.38      .1       0  392.03    .045       0
   424.2      .1       0  599.36      .1       0
#XS Ineff= 2 , 0
          375.78 2215.68  443.12         2216.08
Permanent Ineff=
       F       F
Bank Sta=392.03,424.2
XS Rating Curve= 0 ,0
Exp/Cntr=0.3,0.1

Type RM Length L Ch R = 1 ,362     ,100,99,94.3
XS GIS Cut Line= 5
2227160.96258347343518.4167003932227574.85151947343572.583258733
2227656.79590939343555.9166253952227798.46262081343518.416700393
 2228177.6291853 343401.74993898
#Sta/Elev= 30
       0  2279.4    22.7 2268.62    85.6  2229.1   102.1 2221.91     112 2219.27
   184.8 2213.69   221.2 2214.27   244.4 2211.77   270.9  2211.5   303.9  2208.7
   333.7 2209.56   350.3 2207.14   366.8 2209.03     390 2208.97  449.582204.908
   463.3 2201.76     470 2202.16  478.532205.359   503.5 2207.42   517.1 2206.38
     540 2207.27   564.6 2211.17   580.9 2211.88   625.7 2207.95     773 2212.94
   855.2 2212.23   927.5 2214.26   965.6 2217.08   991.9 2221.06  1044.3  2232.1
#Mann= 5 ,-1 , 0
       0      .1       0   366.8     .06       0  449.58    .045       0
  478.53     .06       0   855.2      .1       0
#XS Ineff= 2 , 0
             433 2211.75     494         2211.75
Permanent Ineff=
       F       F
Bank Sta=449.58,478.53
XS Rating Curve= 0 ,0
Exp/Cntr=0.3,0.1

Type RM Length L Ch R = 1 ,263     ,108.7,108.7,108.7
XS GIS Cut Line= 6
2227210.96281156343558.6945069732227580.40695456343676.750045151
2227679.01830588343640.6388968972227812.35170063343607.305630222
2227942.90721381343567.0278236422228219.29609673343396.194503888
#Sta/Elev= 30
       0 2245.33    33.1 2225.49    57.2 2215.99   122.7 2213.12   136.5 2210.16
   163.7 2208.48   195.1 2210.24   212.2 2206.94     276 2212.55     289    2211
   326.5 2210.83   339.7 2211.01   360.3 2219.75   374.1 2221.46   401.9 2216.58
   408.9 2212.29   418.2 2203.05   440.3 2201.64  457.86 2203.56   509.6  2205.7
   570.5  2202.5   660.4 2205.62     700  2210.3   769.6 2210.89   876.9 2214.68
   919.3 2212.56   983.7 2213.56  1038.9 2219.15  1069.8 2229.04  1091.9 2239.09
#Mann= 7 ,-1 , 0
       0      .1       0     289     .06       0   326.5      .1       0
   418.2    .045       0  457.86      .1       0   769.6     .06       0
   983.7      .1       0
#XS Ineff= 2 , 0
             368 2211.75     507         2211.75
Permanent Ineff=
       F       F
Bank Sta=418.2,457.86
XS Rating Curve= 0 ,0
Exp/Cntr=0.3,0.1

Type RM Length L Ch R = 1 ,154     ,154,154,154
XS GIS Cut Line= 6
2227154.08592565343700.2678531622227566.43102289343778.988280816
2227649.83719028343766.805357489 2227721.9975823343680.587746248
2227963.78175295343570.0042883532228223.37173462343443.489315338
#Sta/Elev= 30
       0 2223.88     6.5  2217.1    23.2 2207.16    34.3 2205.04    69.9 2204.42
    86.7 2198.57   120.1 2202.98   150.2    2202   180.2 2206.03   232.6 2206.28
   290.4 2215.53   300.5 2215.16   340.5 2205.53   350.6 2201.33   367.2 2198.34
   392.4 2199.91     434 2199.01   450.5 2201.53     467 2200.15   478.5 2198.88
  491.26 2200.13   626.8 2203.88   662.8 2202.67   731.7 2205.69   783.6 2205.16
   850.7 2210.65   945.3  2211.5    1014 2214.69    1084 2213.62  1171.5 2215.73
#Mann= 3 , 0 , 0
       0      .1       0     467    .045       0  491.26      .1       0
Bank Sta=467,491.26
XS Rating Curve= 0 ,0
Exp/Cntr(USF)=0,0
Exp/Cntr=0.3,0.1
LCMann Table=0

Chan Stop Cuts=-1
Use User Specified Reach Order=0
Composite Channel Slope=5